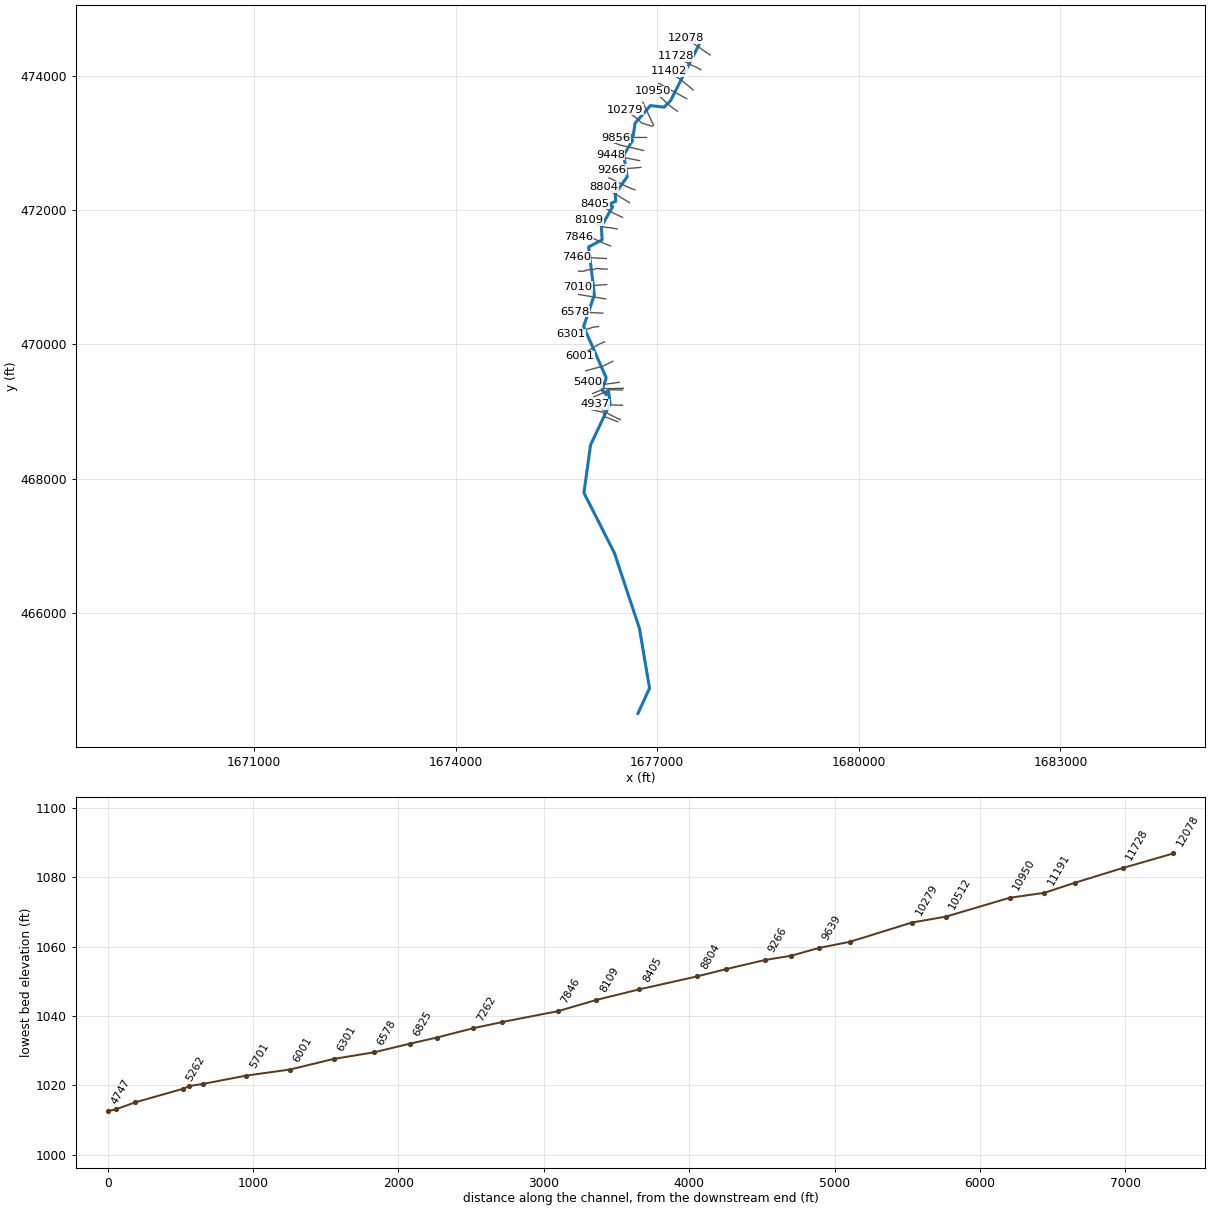
--- FourmileRn.prj (project) ---

Proj Title=FourmileRn
Current Plan=p01
Default Exp/Contr=0,0
English Units
Geom File=g01
Flow File=f01
Plan File=p01
BEGIN DESCRIPTION:
---------- MODELED AS PART OF WVEM CTP PROGRAM, 2025----------
Stream Name: Fourmile Run
Flood Zone: AFH
Marshall County, WV
HEC-RAS Version: RAS 6.6
Vertical Datum: NAVD88
Projection: NAD 1983 StatePlane West Virginia N FIPS 4701 (US Feet)
Terrain: 1-meter West Virginia FEMA R3 South Central (collected 2018-2019)
Land Use: 2024 NLCD
Hydrologic Method:
Duda et al., "Estimation of magnitude and frequency of floods for rural, unregulated streams in and near Virginia and West Virginia." September 8, 2025.
Additional Model Notes:
None
END DESCRIPTION:
DSS Export Rating Curves= 0
DSS Export Rating Curve Sorted= 0
DSS Export Volume Flow Curves= 0
DXF OffsetX= 0
DXF OffsetY= 0
DXF ScaleX= 0
DXF ScaleY= 0

--- FourmileRn.p01 (plan) ---

Plan Title=Floodplain
Program Version=6.60
Short Identifier=Floodplain
Geom File=g01
Flow File=f01
Subcritical Flow
K Sum by GR= 0
Std Step Tol= 0.01
Critical Tol= 0.01
Num of Std Step Trials= 20
Max Error Tol= 0.3
Flow Tol Ratio= 0.001
Split Flow NTrial= 30
Split Flow Tol= 0.02
Split Flow Ratio= 0.02
Log Output Level= 0
Friction Slope Method= 1
Unsteady Friction Slope Method= 2
Unsteady Bridges Friction Slope Method= 1
Parabolic Critical Depth
Global Vel Dist= 0 , 0 , 0
Global Log Level= 0
CheckData=False
Encroach Param=-1 ,0,0, 0
Flow Ratio Tolerance=0.1
Flow Ratio Min Ratio=0.5
Flow Ratio Max Ratio=4
Flow Ratio Max Iterations= 10
Mapping Interval=1HOUR
Computation Time Step Use Courant=        0
Computation Time Step Use Time Series=    0
Computation Time Step Count To Double=0
Computation Time Step Max Doubling=0
Computation Time Step Max Halving=0
Computation Time Step Residence Courant=0
Run HTab= 0
Run UNet= 0
Run Sediment= 0
Run PostProcess= 0
Run WQNet= 0
Run RASMapper=-1
UNET Theta= 0
UNET Theta Warmup= 0
UNET ZTol= 0
UNET ZSATol= 0
UNET MxIter= 0
UNET Max Iter WO Improvement= 0
UNET MaxInSteps= 0
UNET DtIC= 0
UNET DtMin= 0
UNET MaxCRTS= 0
UNET WFStab= 0
UNET SFStab= 0
UNET WFX= 1
UNET SFX= 1
UNET Gravity=32.17405
UNET 1D Methodology=Finite Difference
UNET DSS MLevel= 1
UNET Pardiso=0
UNET DZMax Abort= 0
UNET Use Existing IB Tables= 0
UNET Froude Reduction=False
UNET Froude Limit= 0
UNET Froude Power= 0
UNET D1 Cores= 0
UNET WindReference=Eulerian
UNET WindDragFormulation=Hsu (1988)
UNET D2 Coriolis=0
UNET D2 Cores= 0
UNET D2 Theta= 1
UNET D2 Theta Warmup= 1
UNET D2 Z Tol= 0.01
UNET D2 Volume Tol= 0.01
UNET D2 Max Iterations= 20
UNET D2 Advanced Convergence=0
UNET D2 WS Max Tol=0.15
UNET D2 WS RMS Tol=0.002
UNET D2 WS Stall Tol=1
UNET D2 Equation= 0
UNET D2 RampUpFraction=0.1
UNET D2 TimeSlices= 1
UNET D2 Turbulence Formulation=Non-Conservative (original)
UNET D2 Eddy Viscosity=0.3
UNET D2 Transverse Eddy Viscosity=0.1
UNET D2 Smagorinsky Mixing=0
UNET D2 BCVolumeCheck=0
UNET D2 Cores=0
UNET D2 SolverType=PARDISO (Direct)
UNET D2 Minimum Iterations= 3
UNET D2 Maximum Iterations= 30
UNET D2 Restart Number= 10
UNET D2 Relaxation Coeff=1.3
UNET D2 SOR Precondition Iterations= 10
UNET D2 ILUT Maximum Fill= 8
UNET D2 ILUT Tolerance=1E-08
UNET D2 Convergence Tolerance=0.00001
PS Theta= 1
PS WS Tol= 0.01
PS Volume Tol= 0.01
PS Max Iterations= 20
PS Equation= 0
PS Advance Time Step=-1
PS Target Courant=0.9
PS Time Slices= 1
PS Iterate With 2D=0
PS Project Initial WSE from DS=-1
PS Ramp Up Initial WSE from US=-1
PS Cores=0
UNET D1D2 MaxIter= 0
UNET D1D2 ZTol=0.01
UNET D1D2 QTol=0.1
UNET D1D2 MinQTol=1
Write IC File= 0
Write IC File at Fixed DateTime=0
Write IC File at Sim End=0
Echo Input=False
Echo Parameters=False
Echo Output=False
Write Detailed= 0
HDF Write Warmup=0
HDF Write Time Slices=0
HDF Flush=0
HDF Compression= 1
HDF Chunk Size= 1
HDF Spatial Parts= 1
HDF Use Max Rows=0
HDF Fixed Rows= 1
Calibration Method= 0
Calibration Iterations= 20
Calibration Max Change=0.05
Calibration Tolerance=0.2
Calibration Maximum=1.5
Calibration Minimum=0.5
Calibration Optimization Method= 1
WQ AD Non Conservative
WQ ULTIMATE=-1
WQ Max Comp Step=1HOUR
WQ Output Interval=15MIN
WQ Output Selected Increments= 0
WQ Create Restart=0
WQ Fixed Restart=0
WQ System Summary=0
WQ Write To DSS=0
Sorting and Armoring Iterations= 10
XS Update Threshold= 0.02
Bed Roughness Predictor= 0
Processes Affected by Predictor=Sediment Only
Hydraulics Update Threshold= 0.02
Energy Slope Method= 1
Volume Change Method= 1
Sediment Retention Method= 0
Sediment TS Multiplier= 1
Warm Up Method= 0
XS Weighting Method= 0
Number of US Weighted Cross Sections= 1
Number of DS Weighted Cross Sections= 1
Upstream XS Weight=0
Main XS Weight=1
Downstream XS Weight=0
Number of DS XS's Weighted with US Boundary= 1
Upstream Boundary Weight= 1
Weight of XSs Associated with US Boundary= 0
Number of US XS's Weighted with DS Boundary= 1
Downstream Boundary Weight= 0.5
Weight of XSs Associated with DS Boundary= 0.5
Percentile Method= 0
Sediment Output Level= 3
Mass or Volume Output= 0
Output Increment Type= 1
Profile and TS Output Increment= 1
Transport Output Increment 1
XS Output Flag= 0
XS Output Increment= 10
Read HDF5 Sediment Hotstart= 0
Sediment Hotstart Type= 0
Write Gradation File= 0
Read Gradation Hotstart= 0
Write HDF5 File= 1
Write Binary Output= 1
Write DSS Sediment File= 0
DSS Sediment Output Type= 1
SV Curve= 0
Specific Gage Flag= 0
Subcell Erosion Methods= 0
Subcell Deposition Methods= 0
Advection Scheme= 1
Matrix Solver= 0
Implicit Weighting Factor= 1
Maximum Outer Loop Convergence Iterations= 5
Convergence Maximum Absolute= 0.001
Convergence RMSE= 0.0001
Grain Fractions Max Abs Error= 0.001
Max Subgrid Regions= 1
Max Subgrid Length Scale= 3.402823E+38
Initial Layer Thickness= 3
Min Layer Thickness= 0.1
Max Layer Thickness= 6
Number of Layers= 5

--- FourmileRn.f01 (steady flow) ---

Flow Title=Flow
Program Version=6.60
Number of Profiles= 1
Profile Names=P100yr
River Rch & RM=FourmileRn,Main,12078
     978
River Rch & RM=FourmileRn,Main,8109
    1190
River Rch & RM=FourmileRn,Main,4202
    1370
Boundary for River Rch & Prof#=FourmileRn,Main            , 1
Up Type= 0
Dn Type= 3
Dn Slope=0.023
DSS Import GetInterval= 0
DSS Import GetPeak= 0
DSS Import FillOption= 0

--- FourmileRn.g01 (geometry) ---

Geom Title=Geometry
Program Version=6.60

River Reach=FourmileRn      ,Main
Reach XY= 30
     1677630.952      474477.494     1677200.932       473629.81
     1677104.246      473529.737     1676899.039      473552.705
     1676670.838      473290.476     1676643.076      473101.274
     1676566.215      473126.622      1676635.75       473035.86
     1676501.782      472817.115      1676554.35       472495.17
     1676374.093      472237.808      1676384.56      472128.959
     1676283.037      472084.477     1676337.984      472048.368
     1676169.917      471753.513     1676180.467      471553.837
     1675979.515      471448.128     1676065.766       470736.54
     1675905.532      470264.753     1676241.665         469500.
     1676181.617      469318.798     1676240.519      469249.912
     1676277.126      469300.119     1676298.834      469116.735
     1676008.682      468500.044     1675910.196      467787.363
     1676364.249      466891.019     1676736.579      465766.372
       1676886.3      464880.023     1676714.487      464504.038

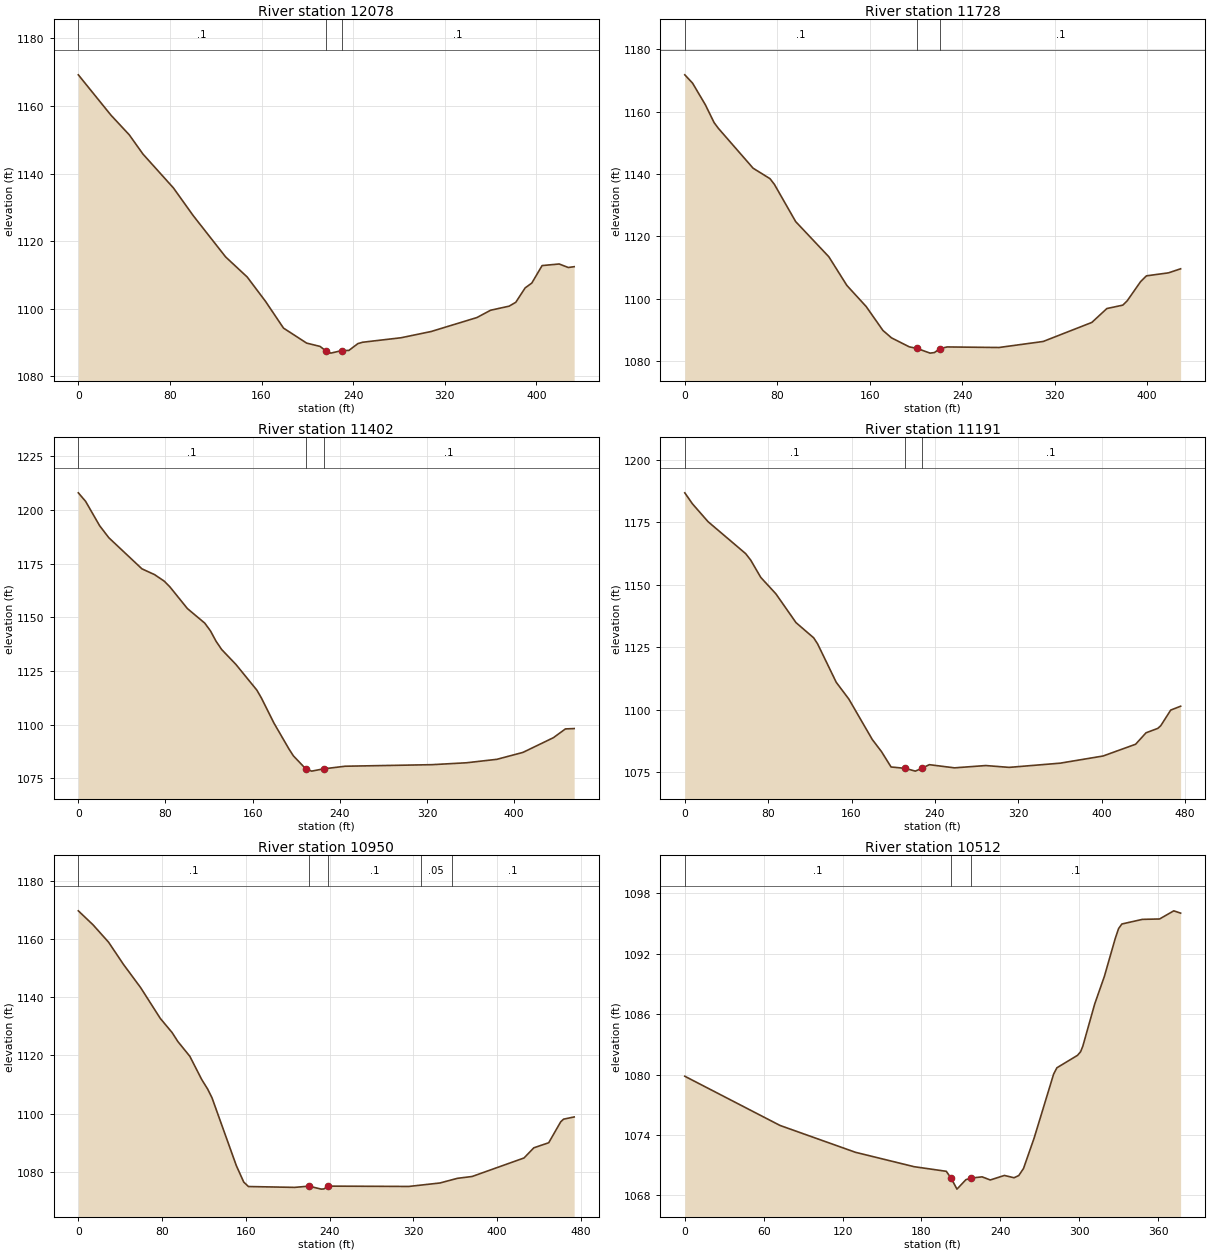
Type RM Length L Ch R = 1 ,12078   ,344.6,349.4,345.8
XS GIS Cut Line= 2
1677784.79286872474306.9100132771677429.13324753474554.035835119
#Sta/Elev= 30
       0 1169.21    28.5 1157.27    44.5 1151.45    56.5 1145.74    83.1 1135.72
   100.4 1127.52   128.7 1115.31   147.5 1109.38   163.6 1102.13   179.2 1094.26
   199.4 1089.82   211.2 1088.83   215.9 1087.59   220.6 1086.85     230  1087.6
   236.3 1087.64   244.2 1089.67   248.3 1090.07   281.9  1091.4   308.2 1093.25
   348.1 1097.37   360.1 1099.54   376.3 1100.75   382.1 1101.89   390.3 1106.16
   396.1 1107.58   405.1 1112.76     420 1113.23     428 1112.19   433.1 1112.43
#Mann= 3 ,-1,0
       0      .1       0   215.9    .045       0     230      .1       0
Bank Sta=215.9,230
XS Rating Curve= 0 ,0
Exp/Cntr(USF)=0,0
Exp/Cntr=0.3,0.1

Type RM Length L Ch R = 1 ,11728   ,321.8,326.4,318.5
XS GIS Cut Line= 6
1677649.11220157474086.7500750451677570.14024666474129.329386208
1677500.20272249474160.2827363791677411.56510449 474206.94077954
1677347.33098099474245.6572375481677272.39084216474290.826766628
#Sta/Elev= 30
       0 1171.76     6.7 1169.11    17.8 1162.16    25.3 1156.49      29 1154.64
    59.1 1141.85    73.7  1138.5    77.5 1136.68    95.9 1124.76   124.6 1113.49
   140.2 1104.31   156.9 1097.55   171.4 1089.89   178.8 1087.52   194.2 1084.64
     201 1084.12   212.2 1082.63   215.9 1082.81   220.9 1084.09     227 1084.61
   271.7 1084.43     310 1086.36   352.1 1092.46   365.1 1096.91   378.9    1098
   382.7 1099.39   394.2 1105.49   399.3 1107.38   418.4 1108.34   428.9 1109.64
#Mann= 3 ,-1,0
       0      .1       0     201    .045       0   220.9      .1       0
Bank Sta=201,220.9
XS Rating Curve= 0 ,0
Exp/Cntr(USF)=0,0
Exp/Cntr=0.3,0.1

Type RM Length L Ch R = 1 ,11402   ,208.7,211.1,210.6
XS GIS Cut Line= 5
1677536.91283859473785.2692626711677469.30503418473840.754059836
1677411.34944142473888.3179410851677333.19769484473951.075033426
1677174.74773246474060.329012325
#Sta/Elev= 30
       0 1208.04     6.7 1204.06    19.5 1192.76      28 1187.12    58.4 1172.63
      70 1169.94    78.9 1166.88      84 1164.27   100.1 1154.14   116.1 1147.33
   121.3 1143.72   126.4 1138.93   131.6 1135.04   144.6 1128.14   163.8 1116.19
     168 1112.52   179.6 1100.75   193.2 1088.85   197.4 1085.53  208.74 1079.48
   214.2 1078.42  225.041079.478   244.9  1080.7   324.4 1081.42   356.3 1082.31
   384.2 1083.92   408.1 1087.14     436 1093.98   447.1 1098.08   455.1 1098.24
#Mann= 3 ,-1,0
       0      .1       0  208.74    .045       0  225.04      .1       0
Bank Sta=208.74,225.04
XS Rating Curve= 0 ,0
Exp/Cntr(USF)=0,0
Exp/Cntr=0.3,0.1

Type RM Length L Ch R = 1 ,11191   ,239.4,240.6,236.8
XS GIS Cut Line= 2
 1677439.6844893473654.6489213171677023.71580509473885.386411452
#Sta/Elev= 30
       0 1186.84     7.3 1182.46    22.3  1175.3    58.4 1162.51    63.3 1159.88
    72.9    1153    87.4 1146.43   106.7 1134.91   123.6 1128.85   127.4 1126.43
   145.3 1111.03   157.4 1104.32   179.9 1088.14   188.7 1083.31   197.9 1077.16
   211.4 1076.61   221.2  1075.5  227.391076.621   234.6 1078.08   258.7 1076.81
   288.7 1077.73   311.2    1077   360.1 1078.68   401.3 1081.55   432.5 1086.25
   442.5 1090.83   453.8  1092.6   456.6 1093.65   466.2 1099.92   475.7 1101.47
#Mann= 3 ,-1,0
       0      .1       0   211.4    .045       0  227.39      .1       0
Bank Sta=211.4,227.39
XS Rating Curve= 0 ,0
Exp/Cntr(USF)=0,0
Exp/Cntr=0.3,0.1

Type RM Length L Ch R = 1 ,10950   ,439.2,438.6,429.8
XS GIS Cut Line= 4
 1677300.3270755473469.1706622141677196.90960832 473542.65184734
1677014.16011407473712.8268351091676933.78849022473767.229264082
#Sta/Elev= 30
       0 1169.67      14 1164.88    28.9 1158.89      43 1151.32    59.5 1143.29
    78.3  1132.7    89.5 1127.88    95.1 1124.75   106.5 1119.69   117.8 1111.75
   123.5 1108.44   127.7 1105.41   150.9 1082.14     158 1076.47   162.5 1074.94
   206.6 1074.65   220.2 1075.07   232.1 1074.05   234.5 1074.11   238.7 1075.08
   315.7 1074.97   345.4 1076.16   362.1 1077.76   376.1 1078.39   425.7 1084.75
   435.1 1088.25   449.3 1089.99   460.8  1097.2   463.5 1098.09   473.6 1098.85
#Mann= 5 ,-1,0
       0      .1       0   220.2    .045       0   238.7      .1       0
  326.86     .05       0  356.86      .1       0
Bank Sta=220.2,238.7
XS Rating Curve= 0 ,0
Exp/Cntr(USF)=0,0
Exp/Cntr=0.3,0.1

Type RM Length L Ch R = 1 ,10512   ,225.3,232.6,226.6
XS GIS Cut Line= 2
1676945.36350119473261.0375942381676786.77864596473603.190764203
#Sta/Elev= 30
       0 1079.83    72.4 1074.94   129.8 1072.27   174.4 1070.84   198.9 1070.38
  202.581069.685     207 1068.61   213.8 1069.55   217.8 1069.71   226.1 1069.83
   232.3 1069.52   243.1 1069.97   250.4 1069.74     254 1069.96   257.6 1070.66
   265.7 1073.69   280.5 1080.04     283 1080.67   298.7 1081.91     301 1082.26
   302.7 1082.81   311.8 1087.03   319.1 1089.75   327.4 1093.53   329.9  1094.5
   332.4 1094.96     348 1095.42   361.1 1095.46   371.9 1096.27   377.1 1096.04
#Mann= 3 ,-1,0
       0      .1       0  202.58    .045       0   217.8      .1       0
Bank Sta=202.58,217.8
XS Rating Curve= 0 ,0
Exp/Cntr(USF)=0,0
Exp/Cntr=0.3,0.1

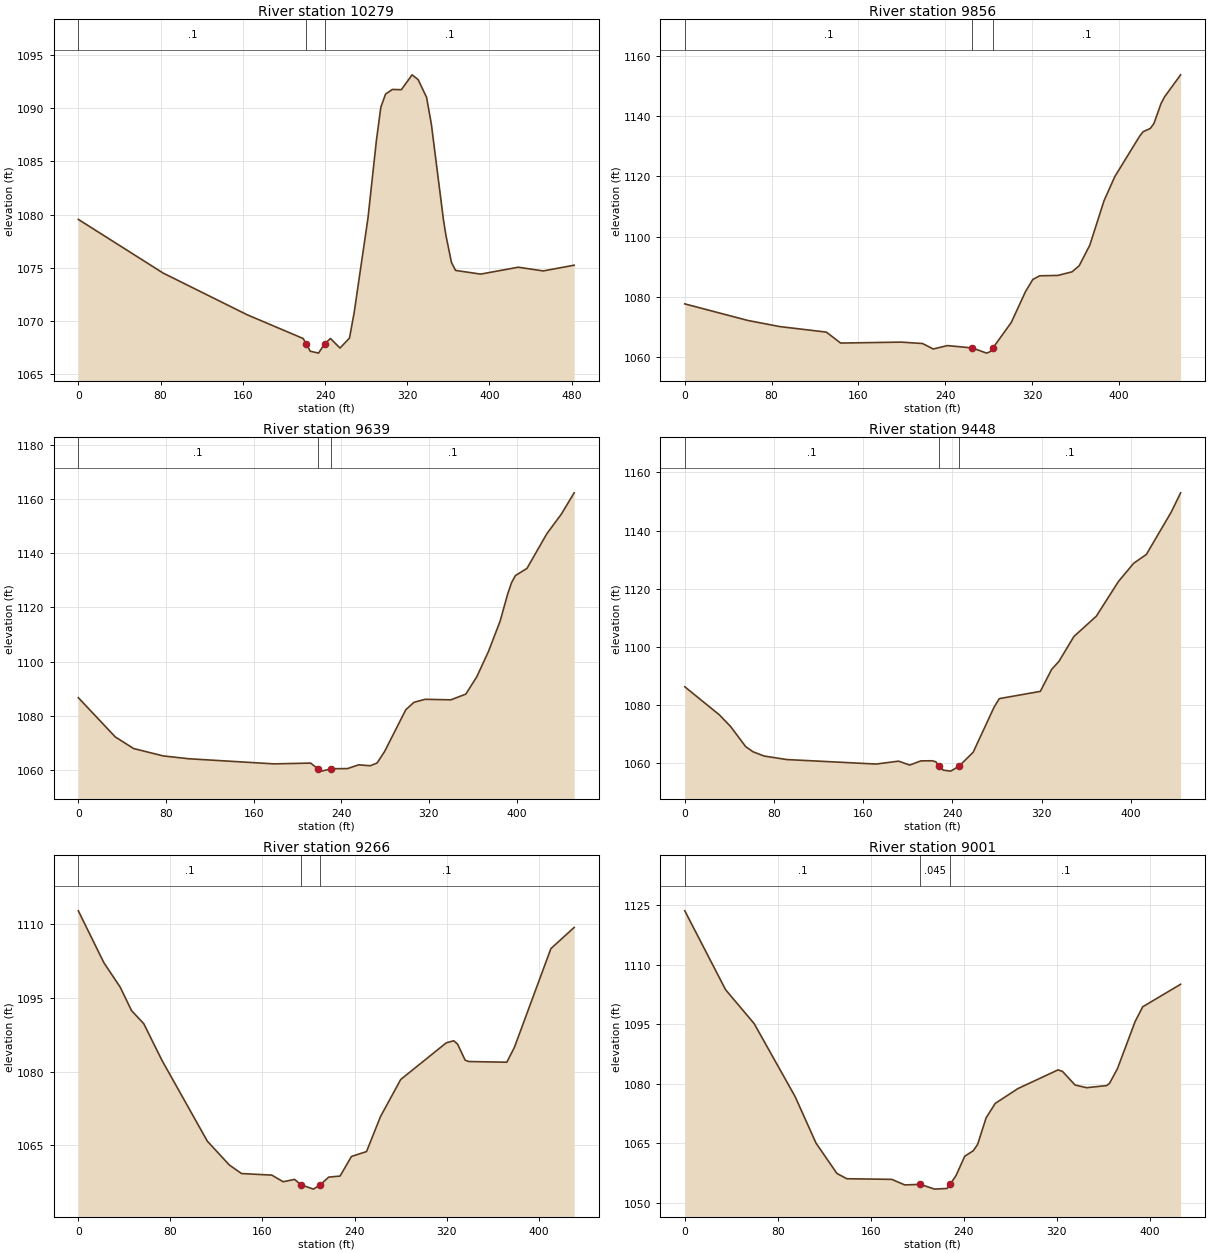
Type RM Length L Ch R = 1 ,10279   ,406.6,423.3,418.3
XS GIS Cut Line= 4
1676928.44392195473245.5296490651676770.96220024473291.888523309
1676684.56339791473373.0746699431676523.14848031 473490.60673646
#Sta/Elev= 30
       0 1079.54    82.5 1074.48   164.2 1070.55   218.7 1068.31   221.81067.813
   225.6 1067.11   233.7 1066.93  239.571067.799   245.3 1068.31   254.6 1067.41
   263.8 1068.35   268.3 1070.71   281.8 1079.66     290 1086.98   294.3 1090.11
   298.9 1091.35   305.5 1091.79   314.3 1091.77   324.7 1093.17   330.6 1092.72
   338.8 1091.05   343.5  1088.5   355.2 1079.53   357.6 1078.06     363 1075.49
     367 1074.73   391.4 1074.38     428 1075.03   452.3 1074.68   482.4 1075.22
#Mann= 3 ,-1,0
       0      .1       0   221.8    .045       0  239.57      .1       0
Bank Sta=221.8,239.57
XS Rating Curve= 0 ,0
Exp/Cntr(USF)=0,0
Exp/Cntr=0.3,0.1

Type RM Length L Ch R = 1 ,9856    ,212,216.3,206.1
XS GIS Cut Line= 2
1676842.03508702473078.5614885361676385.02577936473077.446088683
#Sta/Elev= 30
       0 1077.74    58.3 1072.23    87.6 1070.21   130.5 1068.38   143.6 1064.75
   199.4 1065.06   219.1  1064.6     229 1062.78   242.1 1063.91     265 1063.13
   278.2 1061.41   281.4 1061.89  284.09 1063.17   300.9 1071.57     314 1081.79
   320.8 1085.86   327.1 1087.06   343.8 1087.18   356.9 1088.37   363.5 1090.39
   373.3 1097.22   386.4 1111.94   396.3 1119.93   419.2 1133.35   422.5 1134.86
   429.1 1135.94   432.4 1137.57   438.9 1144.15   442.2 1146.41     457 1153.71
#Mann= 3 ,-1,0
       0      .1       0     265    .045       0  284.09      .1       0
Bank Sta=265,284.09
XS Rating Curve= 0 ,0
Exp/Cntr(USF)=0,0
Exp/Cntr=0.3,0.1

Type RM Length L Ch R = 1 ,9639    ,187.1,191.5,189.1
XS GIS Cut Line= 3
 1676800.1310217472883.8449915861676453.51572718472963.552730262
1676362.71243109472997.496888086
#Sta/Elev= 30
       0  1086.7    33.7 1072.23    50.5 1067.93    77.5 1065.21     101 1064.16
   178.4 1062.28   212.1 1062.56  218.671060.463   222.2  1059.6   230.9 1060.48
   245.8 1060.54   255.9 1061.93   266.5 1061.58   272.7  1062.6   279.5 1066.79
   298.9 1082.24   306.4    1085   316.5  1086.1   340.1 1085.91   353.7 1088.01
   363.8 1094.47   374.4 1103.76     385 1114.92     392 1125.07   395.5 1129.18
     399 1131.76   409.5 1134.39   427.7 1147.21     441 1154.48   452.6 1162.28
#Mann= 3 ,-1,0
       0      .1       0  218.67    .045       0   230.9      .1       0
Bank Sta=218.67,230.9
XS Rating Curve= 0 ,0
Exp/Cntr(USF)=0,0
Exp/Cntr=0.3,0.1

Type RM Length L Ch R = 1 ,9448    ,176.9,181.5,182.2
XS GIS Cut Line= 2
1676738.65507293472732.776903485 1676302.7388481472820.332726421
#Sta/Elev= 30
       0 1086.33      31 1076.69    41.1 1072.67    54.5 1065.81    61.2 1063.99
    71.2 1062.53    91.3 1061.33   171.6 1059.78   191.7 1060.78   201.7 1059.43
   211.7 1060.87   221.8 1060.91   225.1 1060.57  228.141059.014   231.8 1057.69
   238.5 1057.35  245.851059.025   258.6 1063.85   277.3  1079.3     282 1082.26
   318.8 1084.75   328.9 1092.28   335.5 1095.08   348.9  1103.6     369 1110.58
   388.8 1122.48   402.5 1128.77   413.9 1131.81   436.2 1146.37   444.6 1152.97
#Mann= 3 ,-1,0
       0      .1       0  228.14    .045       0  245.85      .1       0
Bank Sta=228.14,245.85
XS Rating Curve= 0 ,0
Exp/Cntr(USF)=0,0
Exp/Cntr=0.3,0.1

Type RM Length L Ch R = 1 ,9266    ,268.7,265.3,258.4
XS GIS Cut Line= 2
1676757.58006207472632.8596812851676328.41459942472595.206026003
#Sta/Elev= 30
       0 1112.71    22.2 1102.16    36.4 1097.18    46.2 1092.43    56.9 1089.74
    72.6 1082.33   112.1 1065.86   131.2 1061.02   141.8 1059.28   168.1 1058.96
     178 1057.61   187.9 1058.09  193.211057.014   204.3 1056.11  210.26 1057.01
   217.5 1058.55   227.4 1058.77   237.3 1062.75   250.4 1063.75   262.6 1070.89
   280.1 1078.41   319.6 1085.85   326.2 1086.29   329.5 1085.61   336.1 1082.33
   339.4 1082.06   372.3 1081.92   378.9 1084.95   410.6 1105.03   430.8 1109.33
#Mann= 3 ,-1,0
       0      .1       0  193.21    .045       0  210.26      .1       0
Bank Sta=193.21,210.26
XS Rating Curve= 0 ,0
Exp/Cntr(USF)=0,0
Exp/Cntr=0.3,0.1

Type RM Length L Ch R = 1 ,9001    ,196,197.4,194.6
XS GIS Cut Line= 6
1676668.81746192472298.3736144161676586.29269259472329.946713999
 1676517.7885645472360.7996706661676428.86551401472406.778909415
  1676361.121555472439.5445919191676281.91666092472477.482180089
#Sta/Elev= 30
       0 1123.61    35.1 1103.74    59.7  1095.2      95 1076.78   112.9 1065.11
   130.9 1057.45   139.4 1056.12   178.1 1055.96   189.3 1054.56  202.691054.704
     215  1053.5   225.8 1053.68  228.33  1054.7   233.5 1056.96   240.9 1061.78
   248.3 1063.18     252 1064.77   259.3 1071.46   267.2 1075.11   286.8 1078.85
   321.2 1083.54     325 1083.17   335.9 1079.72   345.8 1079.06     363 1079.58
   365.5 1080.14   372.3 1083.83   387.6 1095.76   394.1 1099.44   426.7 1105.11
#Mann= 3 ,-1,0
       0      .1       0  202.69    .045       0  228.33      .1       0
Bank Sta=202.69,228.33
XS Rating Curve= 0 ,0
Exp/Cntr(USF)=0,0
Exp/Cntr=0.3,0.1

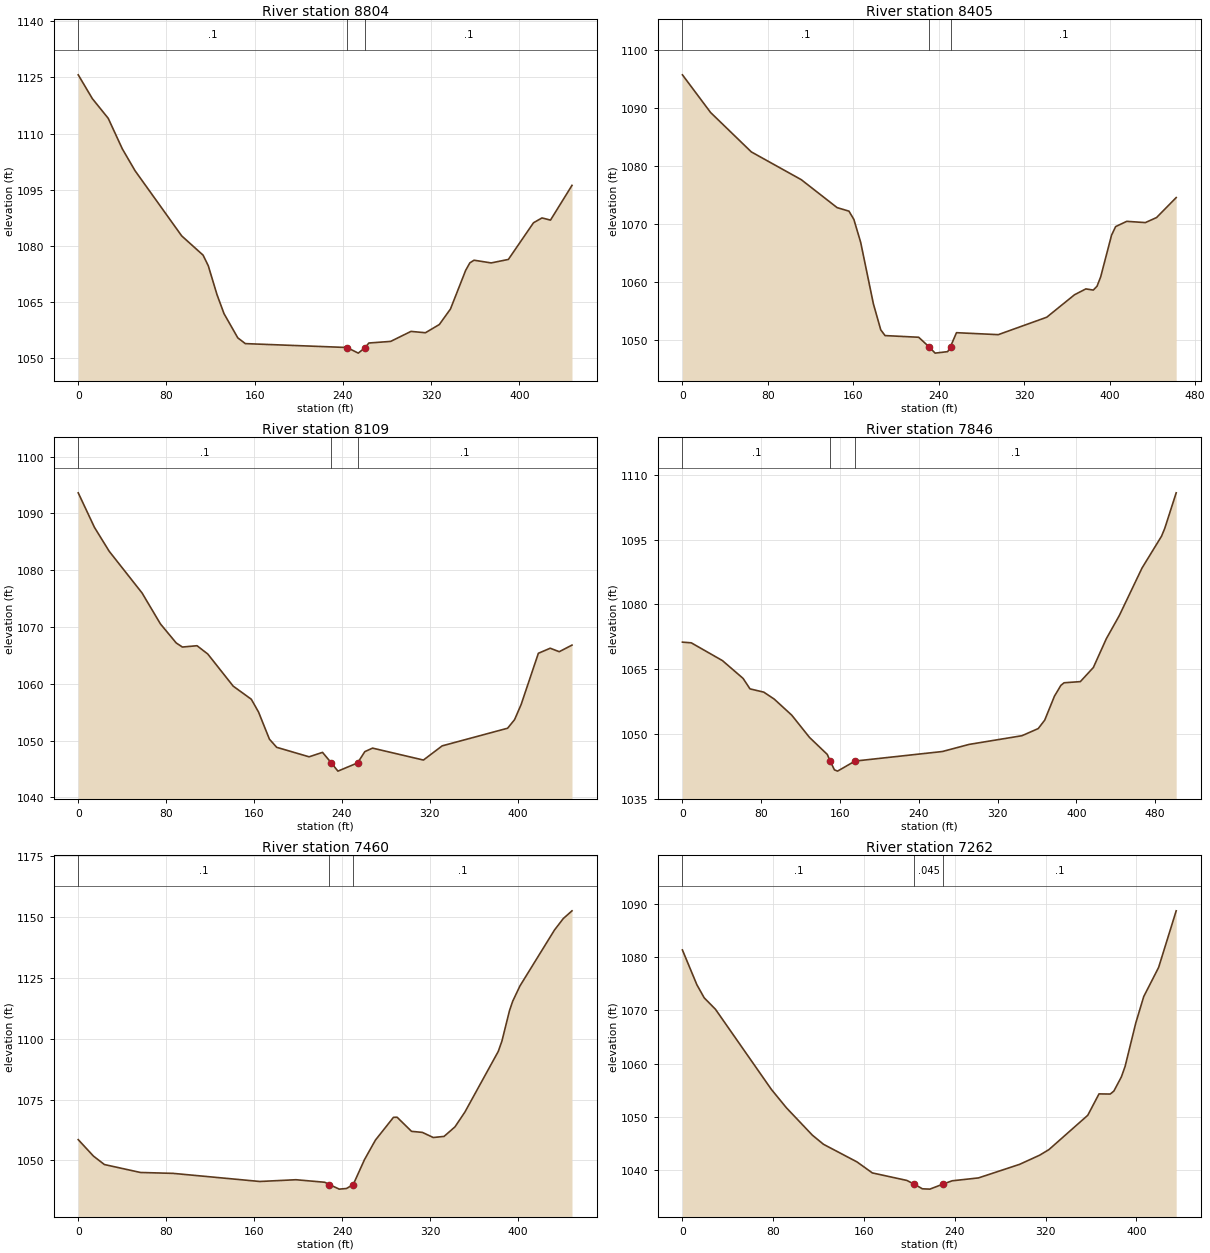
Type RM Length L Ch R = 1 ,8804    ,390.6,398.6,382.1
XS GIS Cut Line= 2
1676588.20383548472107.0958251921676206.01273318472340.210235434
#Sta/Elev= 30
       0 1125.71    12.8 1119.36    27.2  1114.1      40 1105.94    51.6 1100.08
    93.8 1082.72   113.2 1077.58   117.9 1074.76   125.8 1067.06   132.2 1061.95
   144.7 1055.49   151.5 1053.96   243.7 1052.92   253.9 1051.42  260.261052.915
   263.5 1054.12   283.3 1054.55   301.7 1057.22   314.8 1056.86   327.4 1059.05
   337.5 1063.19   351.3 1073.52   355.1 1075.52   358.9 1076.22   374.4  1075.5
     390 1076.43   412.8 1086.22   420.5 1087.51   428.2 1086.93   447.7  1096.2
#Mann= 3 ,-1,0
       0      .1       0   243.7    .045       0  260.26      .1       0
Bank Sta=243.7,260.26
XS Rating Curve= 0 ,0
Exp/Cntr(USF)=0,0
Exp/Cntr=0.3,0.1

Type RM Length L Ch R = 1 ,8405    ,292.4,295.9,290.8
XS GIS Cut Line= 6
1676484.69086167 471889.241886751676399.25599317471928.599747673
1676323.58357234471966.7253275961676229.07490309472029.508994669
1676156.18659742472060.993511751  1676070.783553   472091.447191
#Sta/Elev= 30
       0 1095.73    26.4 1089.22    64.5 1082.42   111.3 1077.62   144.8  1072.8
   155.9 1072.19   160.5 1070.77   166.9  1066.8   178.8 1056.18   185.7 1051.69
   189.7  1050.7   221.2 1050.41   230.7 1048.79   236.6 1047.67   248.4 1047.93
     251  1048.8   256.6  1051.2   295.7 1050.86   341.1 1053.87   367.1 1057.75
   377.7 1058.76   384.7 1058.56   388.2 1059.23   391.6 1060.84   401.8 1068.05
   405.6 1069.52     416 1070.43   433.4 1070.21   443.9 1071.08   462.3 1074.53
#Mann= 3 ,-1,0
       0      .1       0   230.7    .045       0     251      .1       0
Bank Sta=230.7,251
XS Rating Curve= 0 ,0
Exp/Cntr(USF)=0,0
Exp/Cntr=0.3,0.1

Type RM Length L Ch R = 1 ,8109    ,264.4,263.3,258.8
XS GIS Cut Line= 6
 1676404.5801295471716.192692176 1676307.2378045471733.669691339
1676221.62019359471742.2549760041676126.32149968471777.726689845
1676057.91973358471808.7177695931675978.30178259471845.211134925
#Sta/Elev= 30
       0 1093.61    14.8 1087.52    28.2 1083.32    58.1 1075.98    74.8 1070.54
    89.2 1067.18    94.8 1066.47   108.1  1066.7   117.9 1065.24     141 1059.59
   157.5 1057.28   164.1 1055.02     174 1050.25   180.6 1048.82   210.1 1047.15
   222.3 1047.93  230.241046.089   236.3 1044.63  254.181046.074   260.8 1048.06
   267.8 1048.68   314.1 1046.58   331.2 1049.08   390.7 1052.18     397 1053.67
     403 1056.34   418.7 1065.37   429.5 1066.26   437.7 1065.65   449.3 1066.81
#Mann= 3 ,-1,0
       0      .1       0  230.24    .045       0  254.18      .1       0
Bank Sta=230.24,254.18
XS Rating Curve= 0 ,0
Exp/Cntr(USF)=0,0
Exp/Cntr=0.3,0.1

Type RM Length L Ch R = 1 ,7846    ,371.5,385.5,380.2
XS GIS Cut Line= 4
1676306.55506162471464.2043294781676212.79598965471499.573323639
1676032.81164526471581.9065875651675830.59197773471601.081261477
#Sta/Elev= 30
       0 1071.26       9  1071.1    40.6 1066.99    61.6 1062.86    68.6 1060.44
    82.6 1059.68    93.2 1058.07     111 1054.35     129  1049.2   147.1 1045.25
     150 1043.72   154.3 1041.69   157.5 1041.39  175.22 1043.72   263.9 1045.93
   291.1 1047.58   344.7 1049.59   361.2 1051.24   367.8 1053.19   377.7 1058.75
   384.2 1061.24   387.5 1061.85     404 1062.12   417.2 1065.39   430.4 1072.07
   443.6 1077.44   466.6 1088.42   486.4 1095.79   489.7 1097.61   501.3 1105.84
#Mann= 3 ,-1,0
       0      .1       0     150    .045       0  175.22      .1       0
Bank Sta=150,175.22
XS Rating Curve= 0 ,0
Exp/Cntr(USF)=0,0
Exp/Cntr=0.3,0.1

Type RM Length L Ch R = 1 ,7460    ,193.5,197.9,194.3
XS GIS Cut Line= 2
1676243.14662491471275.550133801 1675794.9163159471299.298566385
#Sta/Elev= 30
       0 1058.57    13.9 1051.78    23.8 1048.34    56.6 1045.08    86.3 1044.71
   165.1 1041.38   197.9  1042.1   224.2 1041.06   228.4 1040.11   237.3 1038.24
   243.9  1038.5  250.011040.125   260.3  1050.4   270.2 1058.38   286.6 1067.73
   289.9 1067.78     303 1061.98   312.9 1061.54   322.8 1059.44   332.6  1059.9
   342.5 1063.81   351.5 1069.87   381.9 1094.83   385.2 1099.07   392.1 1111.59
     395 1115.43   401.6 1121.72     433 1144.69     441 1149.39   448.9 1152.56
#Mann= 3 ,-1,0
       0      .1       0   228.4    .045       0  250.01      .1       0
Bank Sta=228.4,250.01
XS Rating Curve= 0 ,0
Exp/Cntr(USF)=0,0
Exp/Cntr=0.3,0.1

Type RM Length L Ch R = 1 ,7262    ,249.5,251.9,252.2
XS GIS Cut Line= 6
1676255.00101832471117.1780055121676087.67107964471127.915151667
1676064.44860647471112.3416328021675956.61926326471107.314471077
1675909.25967703471086.6666039741675829.87800984471087.308613267
#Sta/Elev= 30
       0 1081.29    12.7 1074.79    19.2 1072.32    29.1 1070.18    78.3 1055.18
    91.5 1051.74   114.5 1046.58   124.3 1044.87   153.8 1041.57   167.3 1039.51
   197.7  1038.1  204.131037.413   211.4 1036.53     218 1036.47  229.581037.417
   237.6 1038.03   260.8 1038.57     297 1041.11   314.7 1042.83   322.9 1043.88
   357.1 1050.31     367 1054.32   376.9 1054.29   380.1 1054.85   386.7  1057.5
     390 1059.48   399.4 1067.61   406.4 1072.56   419.5 1078.01     435 1088.63
#Mann= 3 ,-1,0
       0      .1       0  204.13    .045       0  229.58      .1       0
Bank Sta=204.13,229.58
XS Rating Curve= 0 ,0
Exp/Cntr(USF)=0,0
Exp/Cntr=0.3,0.1

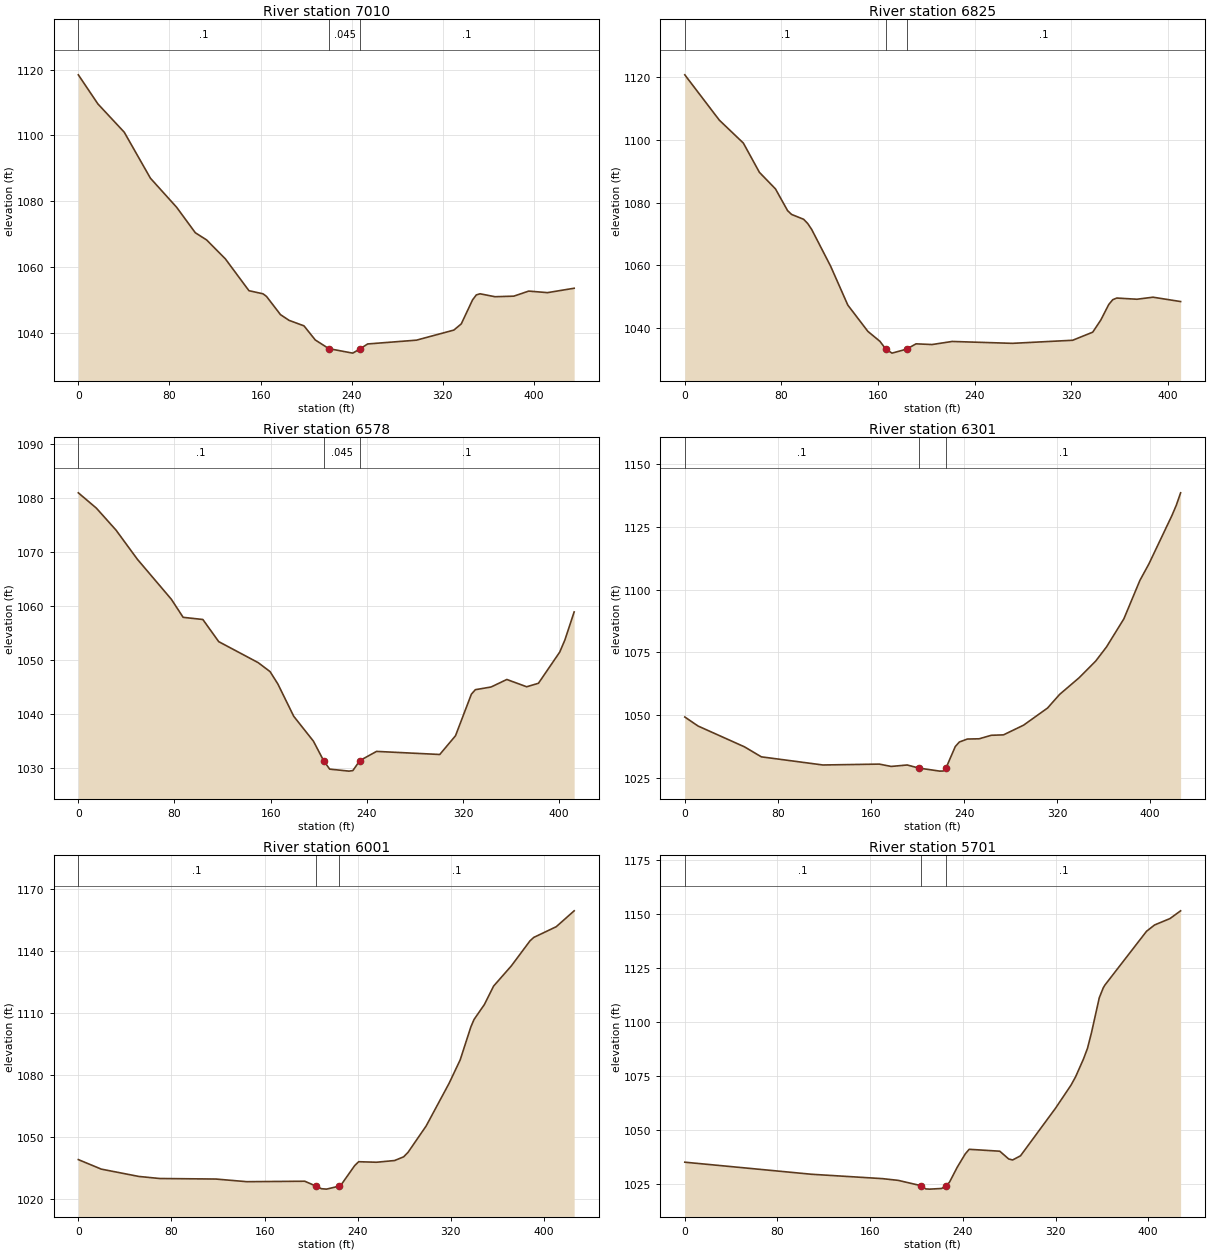
Type RM Length L Ch R = 1 ,7010    ,185.3,185.3,185
XS GIS Cut Line= 2
1676249.71300202470888.0962671451675815.47337806 470857.91745158
#Sta/Elev= 30
       0 1118.42    17.2 1109.56    40.3 1100.97    63.3 1086.97    86.3 1078.13
   102.7 1070.38   112.6  1068.2   129.1 1062.43   149.8 1052.75   162.1 1051.81
   165.2 1051.01   177.5 1045.46     185 1043.73   198.1 1042.06     208 1037.77
  219.961035.118   240.9 1033.76  247.571035.102     254 1036.55   296.8  1037.7
   329.7 1040.77   336.2 1042.66   346.1 1049.95   349.4 1051.47   352.7 1051.81
   365.8 1050.92   382.3 1051.09   395.4 1052.63   411.9 1052.16   435.3  1053.5
#Mann= 3 ,-1,0
       0      .1       0  219.96    .045       0  247.57      .1       0
Bank Sta=219.96,247.57
XS Rating Curve= 0 ,0
Exp/Cntr(USF)=0,0
Exp/Cntr=0.3,0.1

Type RM Length L Ch R = 1 ,6825    ,245.6,246.8,251.9
XS GIS Cut Line= 2
1676234.47645805470674.2220138421675829.36323757470740.867855339
#Sta/Elev= 30
       0 1120.72    28.6 1106.27    48.5 1098.96    61.8 1089.63    75.1 1084.35
    85.1 1077.44    88.4 1076.22    98.4 1074.67   101.7 1073.36   105.1 1071.42
   120.8 1059.69     135 1047.31   151.6 1038.94   161.6 1035.76   166.5 1033.26
   171.6    1032   183.6 1033.26   191.5 1034.96   204.8 1034.74   221.4 1035.72
   271.3 1035.12   321.2  1036.1   337.8 1038.68   344.5 1042.55   351.1 1047.51
   354.4 1049.03   357.7 1049.56   374.4 1049.18   387.7 1049.83   410.6 1048.44
#Mann= 3 ,-1,0
       0      .1       0   166.5    .045       0   183.6      .1       0
Bank Sta=166.5,183.6
XS Rating Curve= 0 ,0
Exp/Cntr(USF)=0,0
Exp/Cntr=0.3,0.1

Type RM Length L Ch R = 1 ,6578    ,272.3,277.6,279
XS GIS Cut Line= 2
1676191.67713922470462.9182289121675779.60595227470482.296517787
#Sta/Elev= 30
       0 1081.01      15 1078.18    31.4  1074.1    49.1 1068.72    77.4 1061.31
    87.2 1057.97   103.6 1057.57   116.8 1053.47   149.6 1049.59   159.5 1047.93
     166 1045.64   179.2 1039.66   195.6 1035.05  204.061031.452   209.1 1029.88
   225.2 1029.51   228.4 1029.61   234.2 1031.46   248.1 1033.16   300.7 1032.59
   313.8 1036.06     327 1043.75   330.3 1044.58   343.4 1045.08   356.5 1046.47
     373 1045.12   382.8 1045.77   400.5 1051.54   404.8 1053.79   412.5 1058.97
#Mann= 3 ,-1,0
       0      .1       0  204.06    .045       0   234.2      .1       0
Bank Sta=204.06,234.2
XS Rating Curve= 0 ,0
Exp/Cntr(USF)=0,0
Exp/Cntr=0.3,0.1

Type RM Length L Ch R = 1 ,6301    ,297.1,300,302
XS GIS Cut Line= 6
1676129.00784601 470264.337656261676041.28820518470251.216619506
1675969.92909592 470228.132348091675874.78361693 470197.35353826
1675803.42450768470174.2695949231675720.17204951470147.338546425
#Sta/Elev= 30
       0 1049.19    11.4 1045.59    51.3 1037.29    65.8  1033.3   118.7 1030.05
   167.2  1030.4   177.4 1029.47   191.2 1030.05   201.11028.828   219.2  1027.6
   222.2 1027.65  224.52 1028.83   232.5  1037.4     236 1039.22   242.9  1040.4
     253  1040.5   263.5  1041.9   273.9 1042.06   291.2 1045.93   311.8 1052.76
   322.2 1058.21     339 1064.87   353.2  1071.5   362.5 1077.15   377.4 1088.34
   391.2 1103.69   398.9 1110.23   418.7 1129.54   422.4 1133.57   426.2 1138.62
#Mann= 3 ,-1,0
       0      .1       0   201.1    .045       0  224.52      .1       0
Bank Sta=201.1,224.52
XS Rating Curve= 0 ,0
Exp/Cntr(USF)=0,0
Exp/Cntr=0.3,0.1

Type RM Length L Ch R = 1 ,6001    ,302.7,299.8,296.8
XS GIS Cut Line= 6
1676214.18680951470035.183915094 1676133.5491755469998.913646415
1676068.66479084469961.239837259  1675983.606562469908.655296758
1675919.81338251469869.2167273461675845.38767834469823.205008343
#Sta/Elev= 30
       0 1038.84    19.7 1034.23    51.9 1030.69    69.8 1029.69   118.1 1029.43
   144.7 1028.15   194.5 1028.37  204.161026.002   208.8 1024.75   213.2 1024.55
  224.111026.004   225.7 1026.61   237.4 1035.95   240.8 1037.81   256.2 1037.56
   271.7 1038.39   279.4 1040.17   283.2 1042.34   298.7 1055.04   318.5 1075.78
     328 1087.09   337.2 1103.08   339.9 1106.64   348.8 1113.88   356.7 1122.79
     372 1132.61   387.9 1144.63   391.2 1146.34   410.5 1151.52   425.9 1159.21
#Mann= 3 ,-1,0
       0      .1       0  204.16    .045       0  224.11      .1       0
Bank Sta=204.16,224.11
XS Rating Curve= 0 ,0
Exp/Cntr(USF)=0,0
Exp/Cntr=0.3,0.1

Type RM Length L Ch R = 1 ,5701    ,302.1,301.1,293.4
XS GIS Cut Line= 6
1676340.09436609469746.9266175931676260.37306884469706.749204502
1676191.56251092469674.0563565051676095.21526267469647.272945508
1676022.87551235469627.4737725111675938.47968376469604.374737337
#Sta/Elev= 30
       0 1035.26   109.2 1029.69   170.6 1027.66   184.2 1026.86  203.661024.431
   208.1  1022.9   211.5 1022.81   221.7 1023.11  225.781024.433   228.5 1026.04
   235.3 1033.06   242.1 1039.09   245.5 1041.22   271.9 1040.34   279.6 1036.74
     283 1036.29   289.8 1038.22     320 1060.21   333.4 1070.89   337.4  1074.8
   344.2 1083.04   347.6 1087.89     351 1095.01   357.8  1111.3   361.2 1115.85
   362.7 1117.18   398.6 1142.02   405.5 1144.92   418.8 1147.88     428 1151.46
#Mann= 3 ,-1,0
       0      .1       0  203.66    .045       0  225.78      .1       0
Bank Sta=203.66,225.78
XS Rating Curve= 0 ,0
Exp/Cntr(USF)=0,0
Exp/Cntr=0.3,0.1

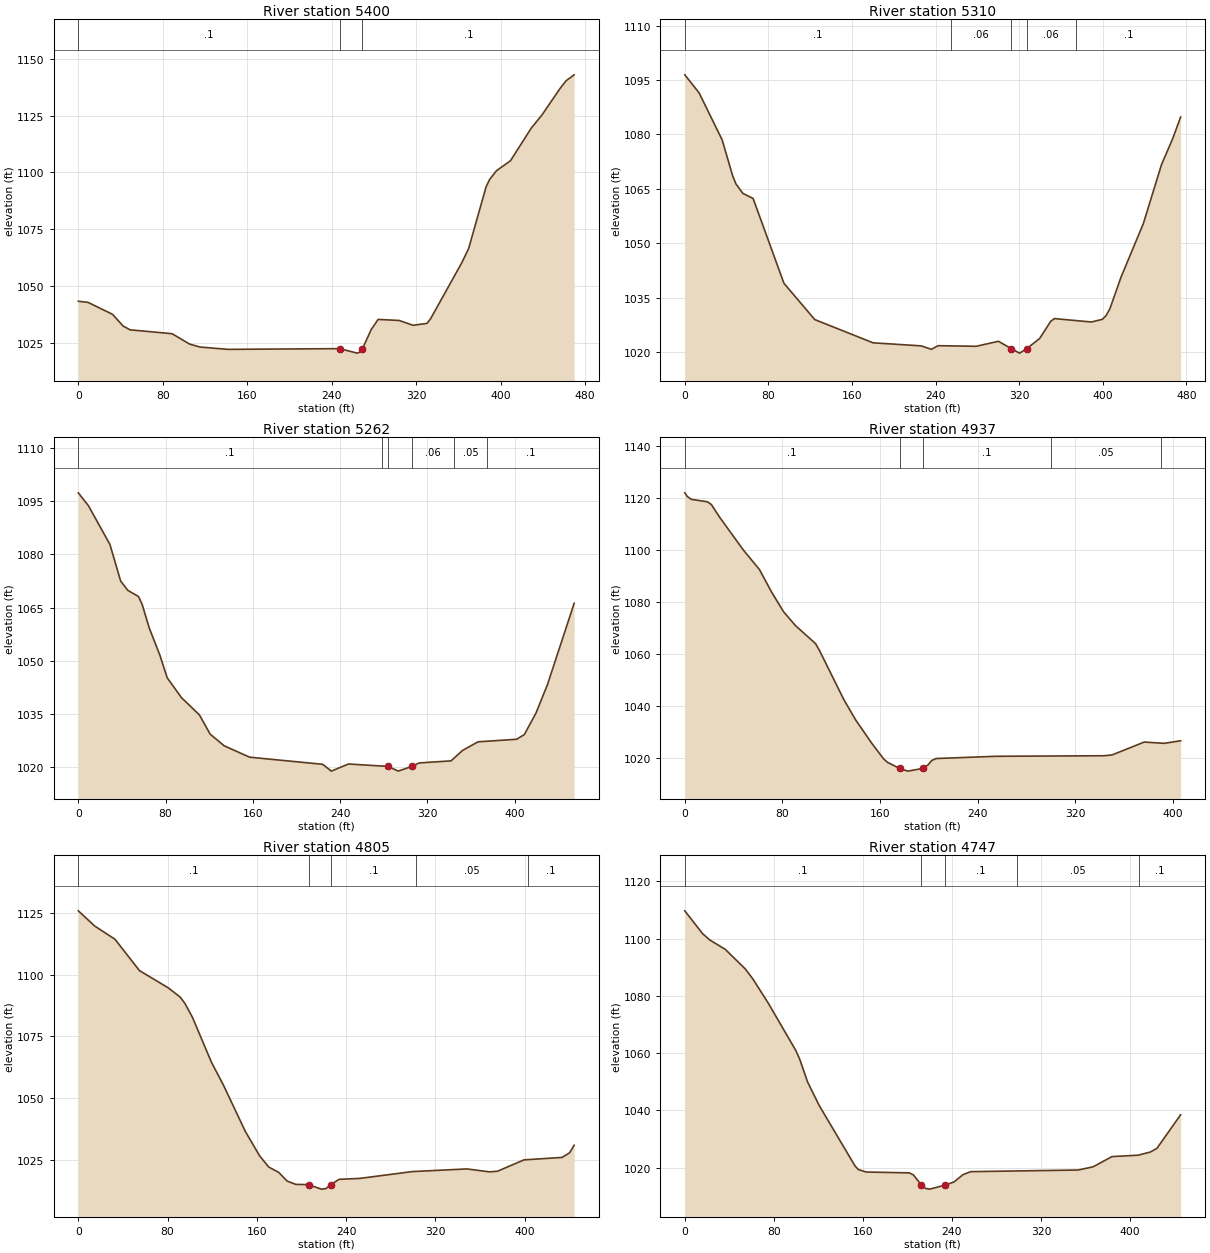
Type RM Length L Ch R = 1 ,5400    ,85.5,90,94.3
XS GIS Cut Line= 6
1676435.14798176469433.8032280951676332.93329117469418.232065007
1676236.78289293469406.3321544231676130.76276375469418.919727668
1676056.14086576 469426.443006591675969.08231284469435.219891921
#Sta/Elev= 30
       0 1043.25     9.2 1042.75    32.4 1037.48    42.4 1032.32      49 1030.65
    88.8 1028.94   105.4 1024.36   115.3 1023.06   141.7 1022.04   247.5 1022.36
     264 1020.38   267.4 1020.96  269.061022.313   277.3 1030.75   283.9 1035.24
   303.7 1034.78     317 1032.66   330.1 1033.48   333.4  1035.4   363.1 1060.23
   369.6  1066.5   386.1 1093.65   389.4 1096.89     396 1100.81   409.2 1105.17
     429 1119.64   438.9 1125.28   456.1    1137     462  1140.5   469.5 1143.05
#Mann= 3 ,-1,0
       0      .1       0   247.5    .045       0  269.06      .1       0
Bank Sta=247.5,269.06
XS Rating Curve= 0 ,0
Exp/Cntr(USF)=0,0
Exp/Cntr=0.3,0.1

Type RM Length L Ch R = 1 ,5310    ,46.5,47.6,48.6
XS GIS Cut Line= 5
1676497.97382228469344.0039878811676323.15428496469339.507506156
1676219.12136195469340.4959872611676159.21222697469313.939735435
 1676038.3885569469265.431229758
#Sta/Elev= 30
       0 1096.43    13.7 1091.47    35.8 1078.49    45.7 1068.73    48.9 1066.42
    55.5 1063.81    65.4 1062.38    94.9 1039.03   124.4 1029.04   180.2 1022.64
   226.2  1021.8     236 1020.85   242.6 1021.85   278.9 1021.68   300.2 1023.06
  312.511021.043   320.4  1019.8  327.171021.007   339.6 1023.81   350.3 1028.58
   353.8 1029.31   389.2 1028.37   399.8 1029.12   403.3 1030.17   406.9 1032.01
   417.5 1040.68   438.9 1055.45   456.3 1071.71     467 1078.84   474.6 1084.81
#Mann= 5 ,-1,0
       0      .1       0  254.88     .06       0  312.51    .045       0
  327.17     .06       0  374.45      .1       0
Bank Sta=312.51,327.17
XS Rating Curve= 0 ,0
Exp/Cntr(USF)=0,0
Exp/Cntr=0.3,0.1

Type RM Length L Ch R = 1 ,5262    ,315.1,325,307.1
XS GIS Cut Line= 5
1676484.58515704469318.7889347171676269.73103806469323.639073419
1676233.57265408469299.663397042 1676176.3796125469266.316911714
1676055.55594242469217.808406037
#Sta/Elev= 30
       0 1097.35     9.3  1093.7      29 1082.81    38.8  1072.5    45.4 1069.89
    55.2 1068.14    58.5 1065.95    65.1 1059.25    74.9 1051.53    81.5 1045.26
    94.6 1039.66     111 1034.82   120.9 1029.38   133.8  1026.1     157  1022.9
   224.1 1020.89     232 1018.97   247.8 1020.98     2841020.297   293.4 1018.99
     306  1020.3   312.6 1021.28   341.8 1021.86   352.3 1024.79   366.5 1027.22
   401.9 1027.94     409 1029.27   419.6 1035.26   430.2 1043.32   454.7 1066.23
#Mann= 6 ,-1,0
       0      .1       0  278.29     .06       0     284    .045       0
     306     .06       0   344.5     .05       0   374.5      .1       0
Bank Sta=284,306
XS Rating Curve= 0 ,0
Exp/Cntr(USF)=0,0
Exp/Cntr=0.3,0.1

Type RM Length L Ch R = 1 ,4937    ,136.1,132.1,126.3
XS GIS Cut Line= 2
1676483.93414282469090.5286500321676078.02907347469105.618057815
#Sta/Elev= 30
       0 1122.03     2.1 1120.59     5.4 1119.52    18.5 1118.59    21.8 1117.51
    28.3 1112.82      48 1100.04    61.2 1092.53      71 1083.98    80.9 1076.35
    90.7    1071   107.1  1064.1   110.4  1061.4   130.1 1042.76     140 1034.75
   153.1 1025.86     163 1019.73   166.2 1018.45  175.991016.121   182.7  1015.1
  194.741016.116   199.1  1017.4   202.3 1019.18   205.9 1019.94   254.9  1020.8
   343.5 1021.01   350.1 1021.33   376.4 1026.27   392.7 1025.78   406.2 1026.76
#Mann= 5 ,-1,0
       0      .1       0  175.99    .045       0  194.74      .1       0
     300     .05       0     390      .1       0
Bank Sta=175.99,194.74
XS Rating Curve= 0 ,0
Exp/Cntr(USF)=0,0
Exp/Cntr=0.3,0.1

Type RM Length L Ch R = 1 ,4805    ,61.5,58.3,49.1
XS GIS Cut Line= 6
1676452.27721259468875.3814446781676373.75210717468913.986354336
1676306.24043117468946.6542680111676220.14414668468998.016369998
1676155.89033817469045.5782827591676057.98567834469073.170091093
#Sta/Elev= 30
       0 1125.79    14.6 1119.66    32.8  1114.3    54.8 1101.59    80.4 1094.67
    91.3 1090.86    95.6 1088.26   102.3 1082.66   119.4 1064.41     130 1055.28
   149.6 1036.56   162.5 1026.59   170.7 1022.05   179.6 1019.89   187.2 1016.37
   194.9 1015.04   206.3 1014.95   217.8 1013.12   221.9 1013.32   226.5 1014.98
   233.7 1017.09   252.2 1017.46   299.3 1020.22   348.3  1021.3   368.4 1020.11
   375.6 1020.35   399.4 1024.96   433.5 1025.95   440.3 1027.83   444.4 1030.89
#Mann= 5 ,-1,0
       0      .1       0   206.3    .045       0   226.5      .1       0
  302.75     .05       0   402.7      .1       0
Bank Sta=206.3,226.5
XS Rating Curve= 0 ,0
Exp/Cntr(USF)=0,0
Exp/Cntr=0.3,0.1

Type RM Length L Ch R = 1 ,4747    ,70.6,74.9,86.8
XS GIS Cut Line= 5
1676414.08753761468845.9617921041676230.49416872468916.996775353
1676205.19375869468968.1476043251676190.89352693468987.947925217
1676028.00315986469024.984034977
#Sta/Elev= 30
       0 1109.72      16 1101.75    22.3 1099.58    36.4 1096.25    54.2 1089.48
      61 1086.02    75.1  1077.4    99.7 1060.97   103.2 1057.94   110.3 1049.95
   120.8 1041.69     153 1020.57     156 1019.35     163  1018.5   201.7 1018.21
   205.3 1017.51   212.6 1013.99   216.3 1012.77     220 1012.53  233.961013.946
   241.9 1015.05     250 1017.61   256.9 1018.63   353.4  1019.2   366.9 1020.34
   383.7 1023.89   407.3 1024.38   418.2 1025.49   424.1 1026.76   445.4  1038.5
#Mann= 5 ,-1,0
       0      .1       0   212.6    .045       0  233.96      .1       0
  298.35     .05       0  408.35      .1       0
Bank Sta=212.6,233.96
XS Rating Curve= 0 ,0
Exp/Cntr(USF)=0,0
Exp/Cntr=0.3,0.1