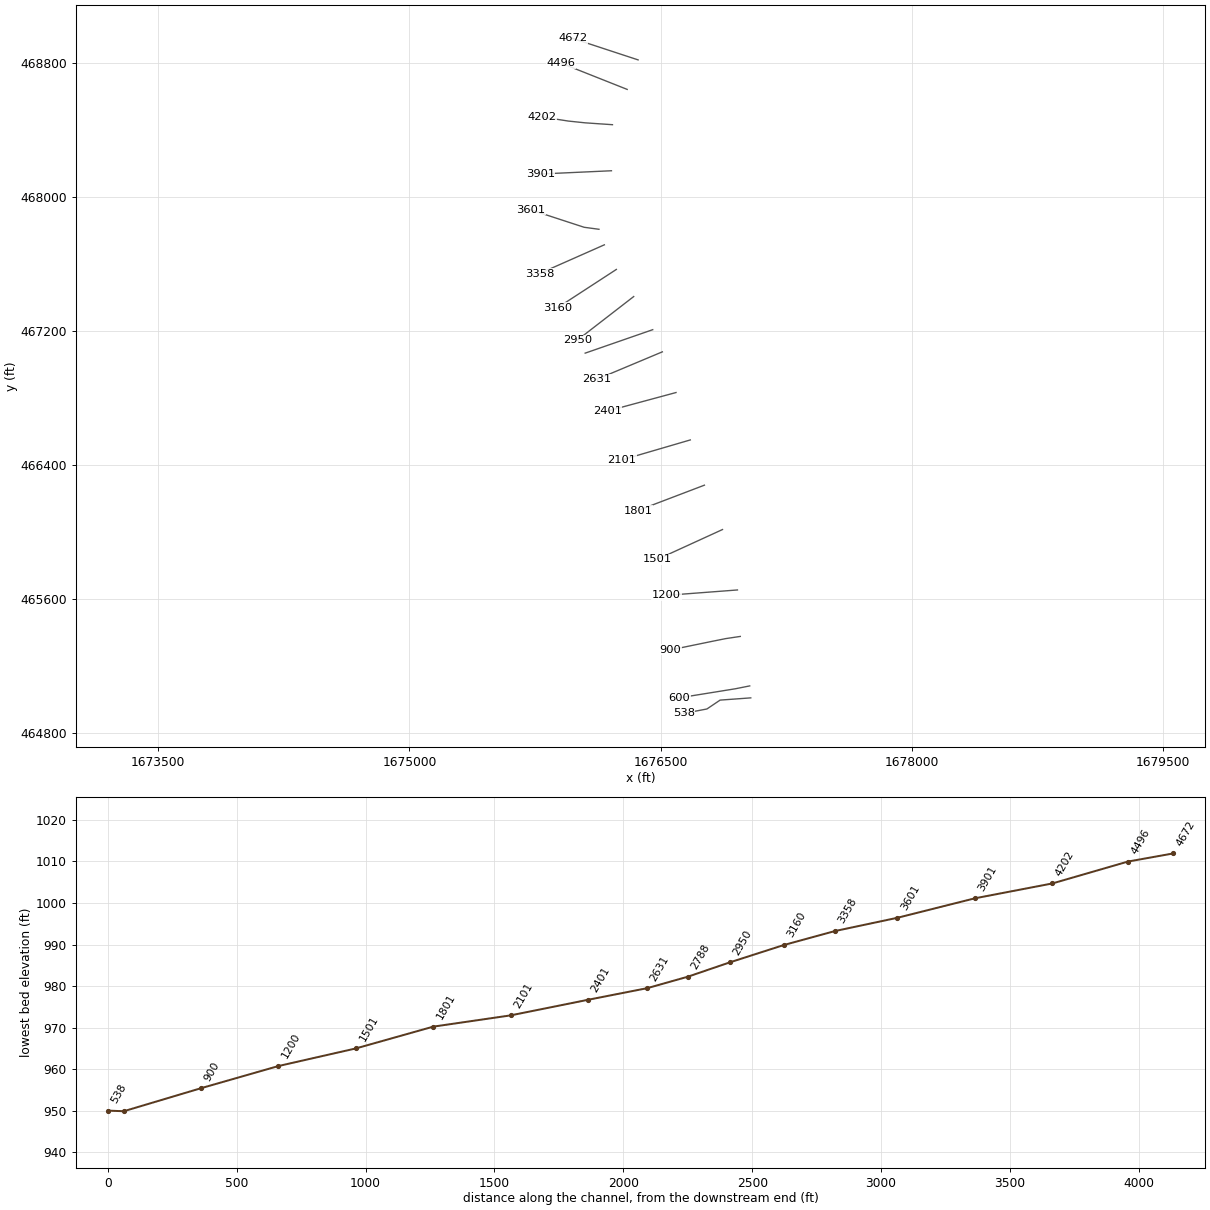
HEC-RAS study FourmileRn.prj: FourmileRn

--- FourmileRn.g01 (geometry) --- (continued)

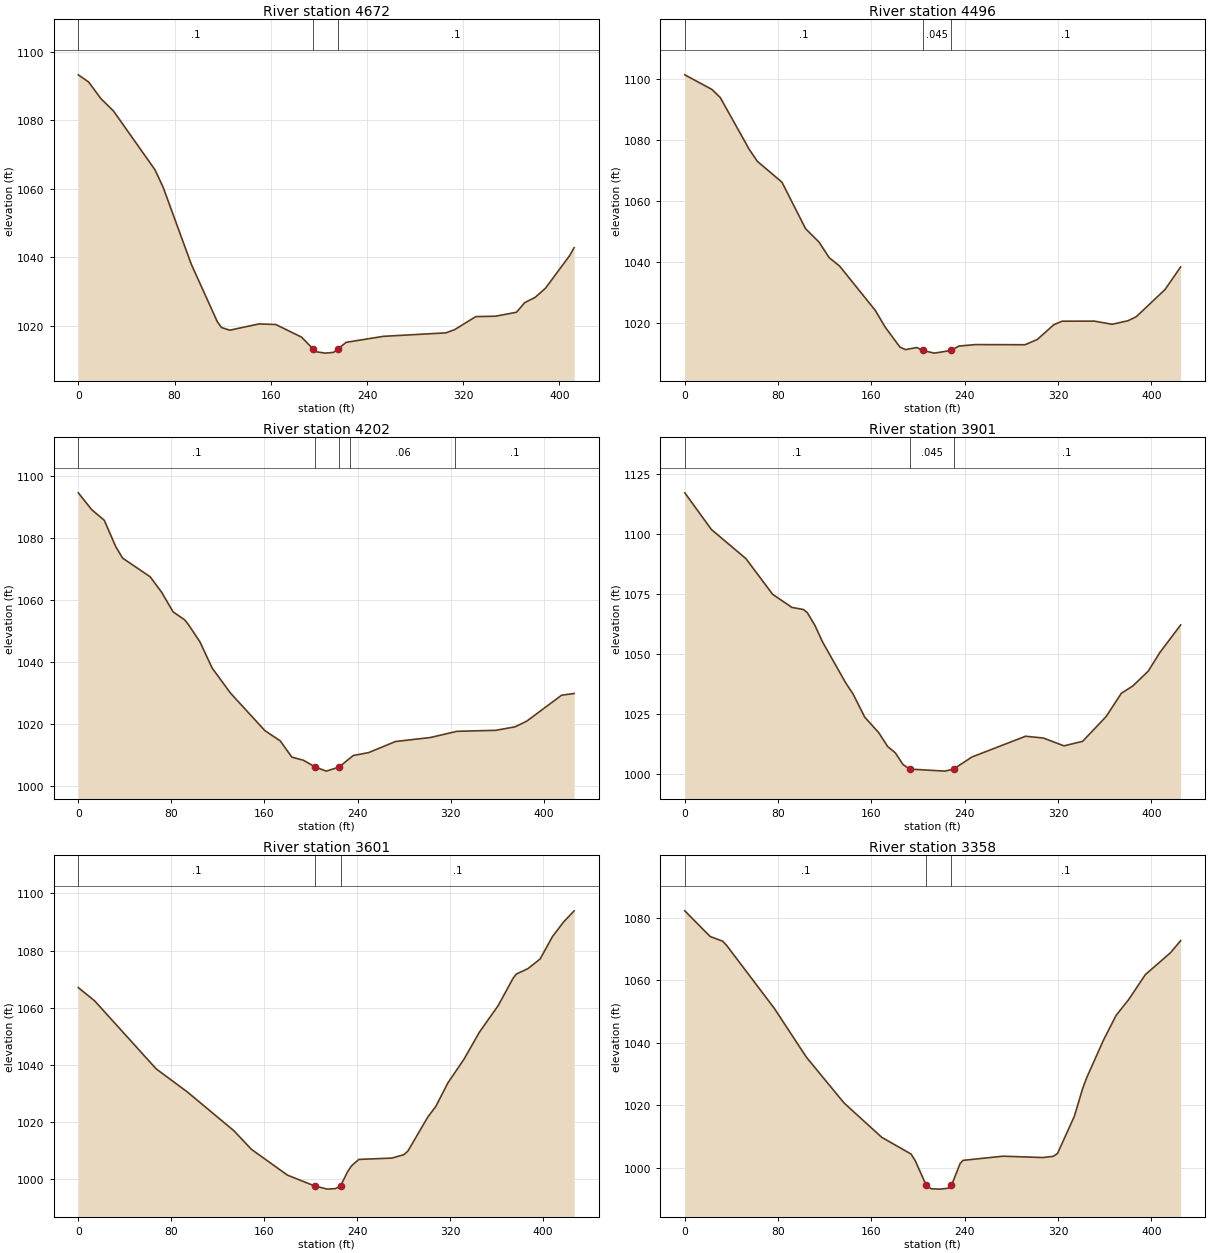
Type RM Length L Ch R = 1 ,4672    ,176.3,176.3,175.1
XS GIS Cut Line= 2
1676365.24635257468817.4451619781675973.64000603468946.147247778
#Sta/Elev= 30
       0 1093.26     8.5 1091.19    18.8 1086.29    29.2  1082.7    63.7 1065.53
    70.5 1060.42    93.9 1037.92   115.5 1021.15     119 1019.42   125.9 1018.63
   150.1 1020.46   164.1  1020.3   185.6  1016.6   195.2 1013.12   198.4 1012.29
   205.3 1011.93   212.2 1012.15     216 1013.17   222.6 1015.08   253.7 1016.84
   305.5 1017.85   312.8 1018.78   330.4  1022.6   346.9 1022.72   364.2 1023.87
   371.1 1026.67   379.8 1028.23   388.4 1030.91   408.4 1040.41   412.2 1042.74
#Mann= 3 ,-1,0
       0      .1       0   195.2    .045       0     216      .1       0
Bank Sta=195.2,216
XS Rating Curve= 0 ,0
Exp/Cntr(USF)=0,0
Exp/Cntr=0.3,0.1

Type RM Length L Ch R = 1 ,4496    ,290.6,293.4,296.1
XS GIS Cut Line= 6
 1676300.1072086468641.2653612491676218.77633452468673.539246842
1676149.06453169468701.2022492591676056.11524252 468738.08636184
1675986.40343969468765.7493642571675905.07256561468798.022921756
#Sta/Elev= 30
       0 1101.24    23.3 1096.44    30.4 1093.79    55.1 1076.88    62.1 1072.91
    83.3 1066.02   103.5 1050.79   115.1 1046.37   123.7  1041.3   132.7 1038.52
   163.3 1023.97   171.7 1018.54   184.4 1011.95   189.2 1011.12   198.9 1011.81
  203.98 1010.84   213.9 1009.97     228 1010.84   234.9 1012.28   249.2 1012.77
   291.6 1012.72   302.2 1014.46   316.3 1019.29   323.4 1020.44   351.1 1020.47
   366.3 1019.43   379.8 1020.58   386.9 1021.89   411.6 1030.81     425 1038.23
#Mann= 3 ,-1,0
       0      .1       0  203.98    .045       0     228      .1       0
Bank Sta=203.98,228
XS Rating Curve= 0 ,0
Exp/Cntr(USF)=0,0
Exp/Cntr=0.3,0.1

Type RM Length L Ch R = 1 ,4202    ,299.3,301.5,303.6
XS GIS Cut Line= 6
1676212.12841468468430.6333184241676124.29591317468436.556206837
  1676049.035565468441.7701071651675949.39107926468452.221529841
1675875.27705425468463.7349582611675788.82611167468477.165377587
#Sta/Elev= 30
       0 1094.48    11.4 1089.09    22.3 1085.61    32.2 1077.11      38 1073.44
    61.8 1067.38    71.6 1062.41    81.5 1056.07    91.4 1053.51    94.7 1051.94
   104.5 1046.43     115 1037.97   130.8 1029.87   160.4 1017.75   173.6 1014.45
   183.5 1009.22   193.4 1008.22  203.791005.995   213.2  1004.7  224.071005.997
   236.3 1009.74   249.5 1010.67   272.6 1014.25   302.5 1015.54   325.5 1017.54
     359 1017.87   375.6 1019.01   385.5 1020.84   415.4 1029.19   426.2 1029.74
#Mann= 5 ,-1,0
       0      .1       0  203.79    .045       0  224.07      .1       0
  233.47     .06       0  323.66      .1       0
Bank Sta=203.79,224.07
XS Rating Curve= 0 ,0
Exp/Cntr(USF)=0,0
Exp/Cntr=0.3,0.1

Type RM Length L Ch R = 1 ,3901    ,306.6,300,293.7
XS GIS Cut Line= 6
1676206.07888609468155.6453513351676118.66994017468151.649296343
1676043.74850209468148.2241063421675943.85237642468143.657186344
1675868.93093833468140.2323244211675781.52199243468136.236269429
#Sta/Elev= 30
       0 1116.98    22.8 1101.72    52.4 1089.59    75.3 1074.72    91.8 1069.29
   101.6  1068.4   104.9 1067.18   111.5 1061.82     118 1054.98   137.8 1037.95
   144.3 1033.16   154.2 1023.62   166.3 1017.08   173.9 1011.34   180.4 1008.76
     187 1003.88  192.621001.959   223.1 1001.11  230.341001.961   246.1 1006.99
   292.1 1015.64   307.4 1014.89     325 1011.63     341 1013.52   361.1  1023.8
   374.2 1033.53   384.1 1036.59   397.2 1042.72   407.1 1050.41     425 1061.97
#Mann= 3 ,-1,0
       0      .1       0  192.62    .045       0  230.34      .1       0
Bank Sta=192.62,230.34
XS Rating Curve= 0 ,0
Exp/Cntr(USF)=0,0
Exp/Cntr=0.3,0.1

Type RM Length L Ch R = 1 ,3601    ,234.9,242.8,251.1
XS GIS Cut Line= 6
1676131.57903509467806.3271523421676043.28754501467818.189661428
1675971.98191334 467841.438630671675876.93223467467872.511403173
1675805.64464758467895.8164746761675722.47617875467923.005068585
#Sta/Elev= 30
       0 1067.02      14  1062.4      67 1038.55    93.7  1030.5   133.9 1016.87
   148.9 1010.38   179.9 1001.34  203.27997.5402   214.4  996.43   221.3  996.62
   225.6 997.542   231.7 1002.57   235.2 1004.66   241.4 1006.84   269.7  1007.3
     280 1008.49   283.5 1009.73   300.7 1021.69   307.6 1025.42     318 1033.67
   331.8 1041.93   345.1 1051.43   361.1 1060.64   374.1 1070.31   376.8 1071.75
     387 1073.72   397.4 1077.09   407.9 1084.88   417.6 1090.07   426.6 1093.92
#Mann= 3 ,-1,0
       0      .1       0  203.27    .045       0   225.6      .1       0
Bank Sta=203.27,225.6
XS Rating Curve= 0 ,0
Exp/Cntr(USF)=0,0
Exp/Cntr=0.3,0.1

Type RM Length L Ch R = 1 ,3358    ,196.7,198.5,200.4
XS GIS Cut Line= 6
1676163.76549437 467713.523620431676083.75778037467678.097510177
1676015.17983354 467647.732085351675923.74235238467607.244633514
1675855.16440554467576.8792086721675775.15669155467541.453098419
#Sta/Elev= 30
       0 1082.15    21.7 1073.96    32.5 1072.44      36 1071.04    76.9  1050.9
   104.2  1035.4   136.5 1020.76   168.8 1009.79   193.9 1004.45   197.5 1002.35
  206.91994.4737   211.2  993.34     219  993.23   226.2  993.54   228.6  994.44
     236 1001.42   238.5 1002.42   272.9 1003.76   306.8 1003.32   315.9 1003.71
   319.5 1004.65   333.9  1016.5     341 1025.35   344.6 1028.93     359 1040.94
   369.7 1048.75   380.5 1053.81   394.8 1061.78   416.4 1068.79     425 1072.62
#Mann= 3 ,-1,0
       0      .1       0  206.91    .045       0   228.6      .1       0
Bank Sta=206.91,228.6
XS Rating Curve= 0 ,0
Exp/Cntr(USF)=0,0
Exp/Cntr=0.3,0.1

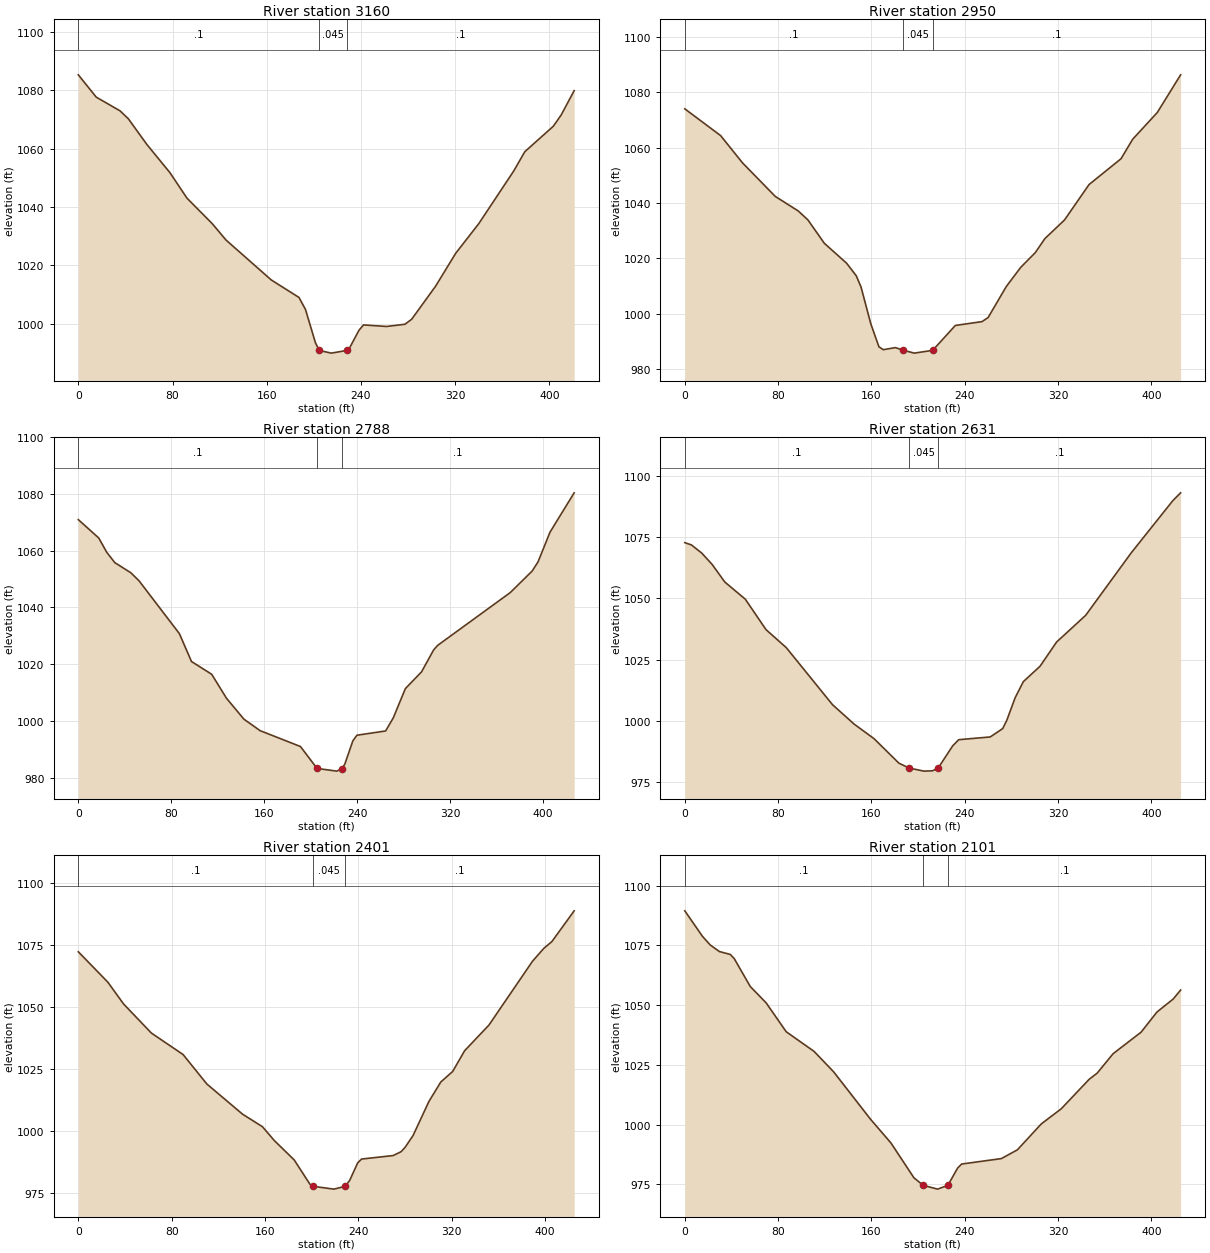
Type RM Length L Ch R = 1 ,3160    ,208.3,209.3,210.2
XS GIS Cut Line= 2
1676235.38338783467566.5492147061675882.45890581 467336.85489624
#Sta/Elev= 30
       0 1085.29    15.2 1077.64    35.4 1072.95    42.5 1070.21    58.2 1061.42
    77.8 1051.74    92.3 1042.99   113.7 1034.27   125.5 1028.61   163.9 1014.94
   187.4 1008.95   192.9 1004.86   201.4  993.38  204.59990.7883   214.8  989.86
  227.87990.7642   230.5  991.74   238.3  997.67   242.2  999.53   261.8     999
   277.4  999.76   283.1 1001.47   303.4  1012.8   320.5 1024.09   340.1 1034.26
   369.8 1052.33   379.2 1058.93   403.4 1067.66   410.1 1071.54   421.1 1079.86
#Mann= 3 ,-1,0
       0      .1       0  204.59    .045       0  227.87      .1       0
Bank Sta=204.59,227.87
XS Rating Curve= 0 ,0
Exp/Cntr(USF)=0,0
Exp/Cntr=0.3,0.1

Type RM Length L Ch R = 1 ,2950    ,165.8,161.8,158
XS GIS Cut Line= 6
1676338.91436348467404.6886262531676269.70584047467351.149691337
 1676210.3844368467305.2593631681676131.28879447467244.071821504
1676071.96706273467198.1814933351676002.75821164467144.642558419
#Sta/Elev= 30
       0 1074.06    30.7 1064.38    49.5  1054.5    77.6 1042.36    97.2 1037.13
   105.5  1033.9   119.6 1025.43   138.7 1018.21     147 1013.65   151.1 1009.57
   159.4  996.35   166.4  987.99   170.1  986.93   180.5  987.69  187.22986.7405
   196.7  985.69  212.47986.6937   231.9   995.7   254.8  997.09     260  998.57
   275.6  1009.8     288 1016.75   300.4 1022.03   308.7 1027.14   325.5 1033.87
   346.5 1046.67   373.9    1056   383.9 1063.06     405 1072.73     425 1086.36
#Mann= 3 ,-1,0
       0      .1       0  187.22    .045       0  212.47      .1       0
Bank Sta=187.22,212.47
XS Rating Curve= 0 ,0
Exp/Cntr(USF)=0,0
Exp/Cntr=0.3,0.1

Type RM Length L Ch R = 1 ,2788    ,158.1,157.6,159.1
XS GIS Cut Line= 2
1676452.50319981467206.9183292241676049.28069185467066.922157021
#Sta/Elev= 30
       0    1071    17.6 1064.51    24.5 1059.46    31.4 1055.84    45.3 1052.22
    52.3  1049.4      87 1030.77    97.4 1020.94   114.8 1016.43   127.6 1007.94
   142.6 1000.57   156.5  996.54   191.2  990.94   205.5983.2117   222.5  982.26
  226.94983.1771   229.4  984.76   236.3  992.93   239.8  994.93   264.5  996.43
   271.1 1001.05   281.5 1011.37   295.4 1017.27   305.8    1025   309.3 1026.63
   371.8 1045.26   390.6 1052.84   395.7 1056.08     406 1066.56   426.8 1080.46
#Mann= 3 ,-1,0
       0      .1       0   205.5    .045       0  226.94      .1       0
Bank Sta=205.5,226.94
XS Rating Curve= 0 ,0
Exp/Cntr(USF)=0,0
Exp/Cntr=0.3,0.1

Type RM Length L Ch R = 1 ,2631    ,232,230,228.6
XS GIS Cut Line= 6
1676509.98104551467074.6507443871676429.30043259 467040.78499847
1676360.14571527467011.7574974691676267.93920676466973.053834715
1676198.78448944466944.0260056351676118.10387651466910.160259718
#Sta/Elev= 30
       0 1072.66     5.6 1071.77    14.3 1068.52    23.4 1063.82    34.3 1056.62
    51.9  1049.6    69.6 1037.21      87 1029.85   126.6  1006.6   145.2  998.66
   162.2  992.74   183.5  982.76  192.08 980.794   204.9   979.5   212.3  979.62
   217.3  980.83   217.3  980.84   229.6  989.79   234.8  992.32   261.8  993.44
   272.5  996.85     276 1000.21   283.1 1009.37   290.2    1016   304.5 1022.27
   318.7 1032.15   343.6 1043.03   382.7 1068.54   418.3 1089.79     425 1092.99
#Mann= 3 ,-1,0
       0      .1       0  192.08    .045       0   217.3      .1       0
Bank Sta=192.08,217.3
XS Rating Curve= 0 ,0
Exp/Cntr(USF)=0,0
Exp/Cntr=0.3,0.1

Type RM Length L Ch R = 1 ,2401    ,299.7,300,300.4
XS GIS Cut Line= 6
1676591.53776084466831.7041015921676507.06581692466808.884593427
1676434.66143417 466789.324921251676338.12192909466763.245249003
1676265.71754634466743.6855768411676181.24560243466720.866068676
#Sta/Elev= 30
       0 1072.42    25.3 1060.17    38.8 1051.37    62.6 1039.65    89.8 1030.98
   110.2 1019.08   140.8 1006.92   157.8 1001.88     168  996.29     185   988.5
   198.6  978.62  201.42977.8306     219   976.7  228.81977.8325   232.6  980.24
   239.5  987.32   242.8  988.83   269.9  990.24   276.7  991.81   280.1  993.57
   286.9   998.3   300.5 1012.05   310.7 1019.91   320.9 1024.17   331.1 1032.51
   351.9 1042.83   389.3 1068.61   399.1 1073.85   405.9 1076.53     425 1088.94
#Mann= 3 ,-1,0
       0      .1       0  201.42    .045       0  228.81      .1       0
Bank Sta=201.42,228.81
XS Rating Curve= 0 ,0
Exp/Cntr(USF)=0,0
Exp/Cntr=0.3,0.1

Type RM Length L Ch R = 1 ,2101    ,299.3,300,301.1
XS GIS Cut Line= 6
1676676.77315468466548.7401005921676592.78578985466524.196186423
1676520.79708867 466503.158170761676424.81171633466475.107701927
1676352.82268709466454.0700143431676268.83565034466429.525772095
#Sta/Elev= 30
       0 1089.46    15.1 1078.81    21.8 1075.16    29.7 1072.41      39  1071.2
    42.4 1069.44    56.1 1057.79    69.8 1050.89    86.9 1038.85   110.8 1030.62
   127.6 1022.05   159.3 1002.15   176.7  992.28   196.4   977.7  204.34974.5477
   216.7  972.95  225.54974.5501   233.8  981.73   237.3  983.45   271.4  985.74
   285.1  989.41   305.6 1000.27   322.7 1006.59   346.6 1018.92   353.5 1021.53
   367.1 1029.63   391.1 1038.65   404.7 1047.09   418.6 1052.52     425  1056.3
#Mann= 3 ,-1,0
       0      .1       0  204.34    .045       0  225.54      .1       0
Bank Sta=204.34,225.54
XS Rating Curve= 0 ,0
Exp/Cntr(USF)=0,0
Exp/Cntr=0.3,0.1

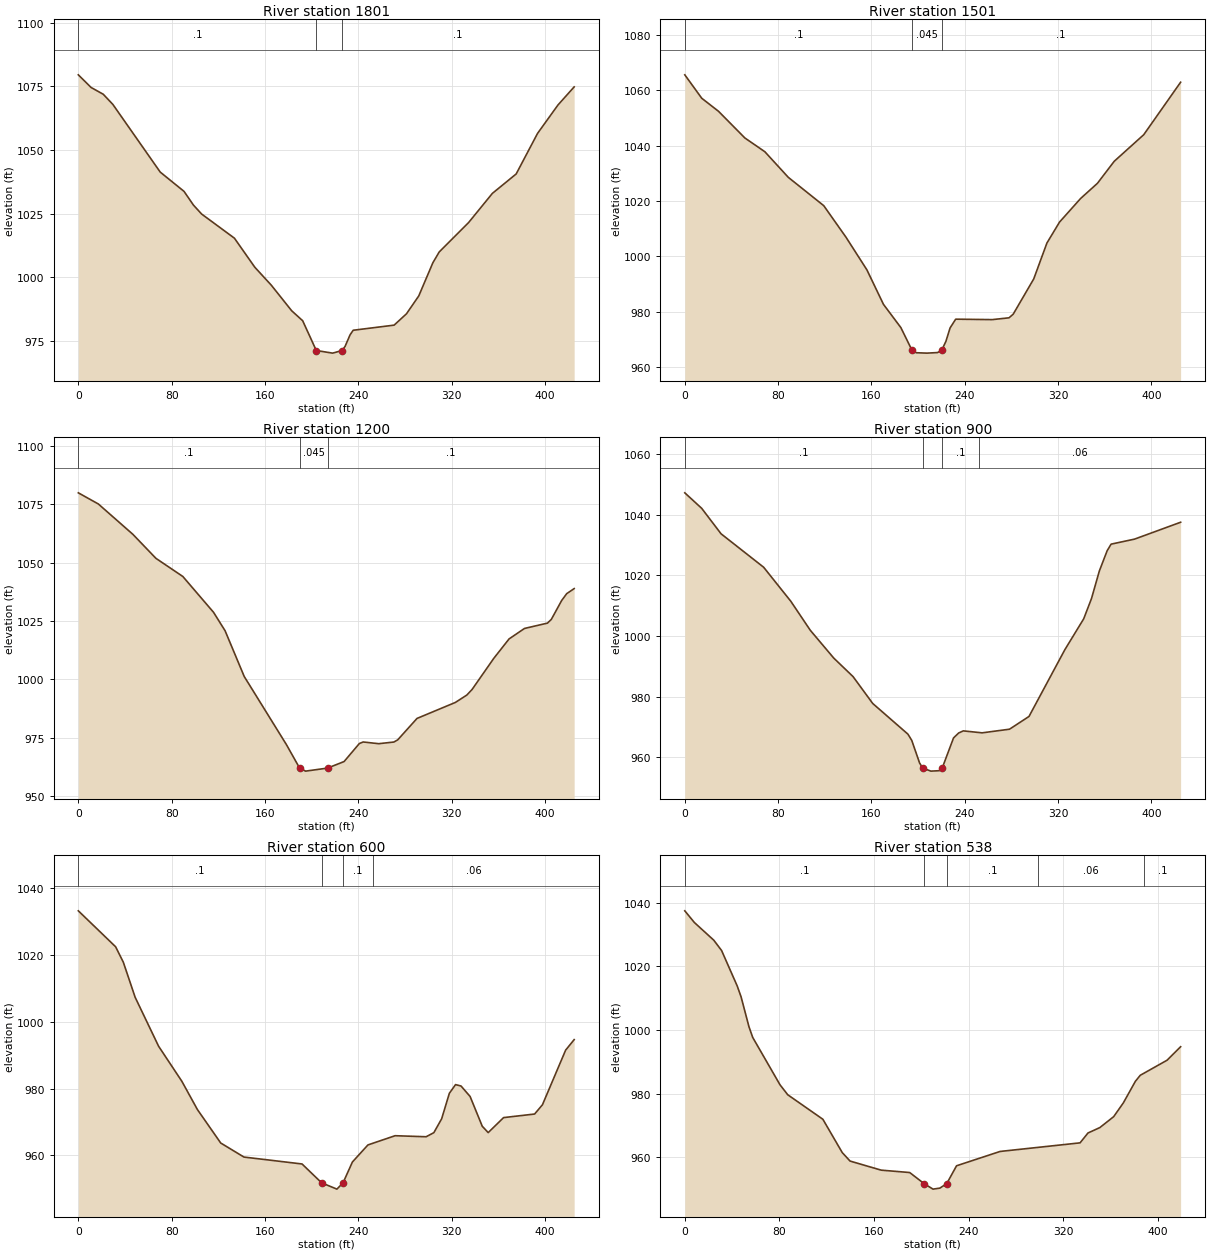
Type RM Length L Ch R = 1 ,1801    ,299.2,300,300.7
XS GIS Cut Line= 6
1676761.04529583466278.7298138441676679.28496067466247.561569095
1676609.20439218466220.8457432541676515.76396225466185.225079596
1676445.68306567466158.5095818341676363.92240243466127.341337085
#Sta/Elev= 30
       0 1079.51    10.9 1074.56    21.4 1071.87    29.6 1067.89    70.2 1041.32
    90.6 1033.75    98.7 1028.35   105.7 1024.85   133.8 1015.37   151.3 1003.95
   165.4  996.92   182.9  986.86   192.3  982.96  203.97971.2632     218  970.24
  225.92971.2596   228.6  972.84   232.9   977.4   235.6  979.22   270.7  981.23
   281.3   985.7   291.8  992.69   303.9 1005.72   309.3 1009.94   334.6 1021.55
   354.9 1032.96   375.3 1040.59   393.6 1056.49   411.1 1067.65     425 1074.77
#Mann= 3 ,-1,0
       0      .1       0  203.97    .045       0  225.92      .1       0
Bank Sta=203.97,225.92
XS Rating Curve= 0 ,0
Exp/Cntr(USF)=0,0
Exp/Cntr=0.3,0.1

Type RM Length L Ch R = 1 ,1501    ,305.9,300.6,297.3
XS GIS Cut Line= 6
1676869.06214017466013.8569840041676789.49766676465977.446295679
1676721.29964042465946.2370405051676630.36871992465904.624919012
1676562.17036551465873.4156638381676482.60589209465837.004975513
#Sta/Elev= 30
       0 1065.57    14.5 1057.12    28.9 1052.39    51.5 1042.75    68.6 1037.79
    88.7 1028.53   119.1 1018.29   138.2 1006.87   156.1  995.09   170.3  982.62
   185.2  974.23  194.82965.9724   198.5  965.14   207.5     965   216.6   965.2
  220.14 965.976   223.8  969.24   227.4  974.11   232.2  977.27   263.5  977.11
   277.9  977.76   281.5  979.08   299.1  991.82   310.4 1004.79   321.2 1012.35
   339.2 1020.85   353.7 1026.37   368.1 1034.33   393.4 1043.94     425  1062.9
#Mann= 3 ,-1,0
       0      .1       0  194.82    .045       0  220.14      .1       0
Bank Sta=194.82,220.14
XS Rating Curve= 0 ,0
Exp/Cntr(USF)=0,0
Exp/Cntr=0.3,0.1

Type RM Length L Ch R = 1 ,1200    ,299.4,300.2,301.1
XS GIS Cut Line= 6
1676958.28998008 465653.151012511676871.04113884465646.524713427
1676796.25651151465640.8446066681676696.54378442465633.271787167
1676621.75915709465627.5916804221676534.51031584465620.965381339
#Sta/Elev= 30
       0 1079.86    17.2 1075.07    46.8 1062.08    66.5 1051.83    89.6 1044.05
   115.9 1028.73   125.8 1020.83   142.2 1001.26   178.4  972.08  189.68962.0576
   194.8  960.76  213.64962.0569   227.8  964.86   240.9  972.58   244.2  973.23
   257.4   972.5   270.5  973.21   273.8  974.16   290.3  983.31   323.2  990.16
     333  993.31   337.5   995.7   356.1 1009.02   369.2 1017.33   382.4 1021.81
   402.1  1024.1   405.4 1025.67   414.3 1033.78   418.6  1036.7     425 1038.87
#Mann= 3 ,-1,0
       0      .1       0  189.68    .045       0  213.64      .1       0
Bank Sta=189.68,213.64
XS Rating Curve= 0 ,0
Exp/Cntr(USF)=0,0
Exp/Cntr=0.3,0.1

Type RM Length L Ch R = 1 ,900     ,300.3,300,299.5
XS GIS Cut Line= 6
1676975.23318768465375.7716460081676888.57095942 465362.79430975
1676815.03501725465348.0440111761676717.08409767465327.904287666
1676643.62066193465312.7996590881676557.91348426465295.177647084
#Sta/Elev= 30
       0 1047.17    14.5 1042.05    31.1 1033.66    67.6 1022.64    90.9 1011.42
   107.6 1001.86   127.7   992.7   144.3  986.57   161.1  977.74   191.3  967.62
   194.6  965.55   201.3  958.11  204.01956.4297     211  955.43   218.1  955.57
  220.69956.4286   230.4  966.37   234.8     968   238.8   968.7   254.9  968.05
   278.4  969.25   295.1  973.45   325.8  995.43     342 1005.64   348.7 1012.33
   355.4 1021.38   362.1 1028.07   365.5 1030.25   385.6 1031.91   425.1 1037.47
#Mann= 4 ,-1,0
       0      .1       0  204.01    .045       0  220.69      .1       0
  252.63     .06       0
Bank Sta=204.01,220.69
XS Rating Curve= 0 ,0
Exp/Cntr(USF)=0,0
Exp/Cntr=0.3,0.1

Type RM Length L Ch R = 1 ,600     ,60.3,62.1,68.3
XS GIS Cut Line= 6
1677031.55197267465080.4231553381676945.68993968465063.256194919
1676871.64678067465051.3136335021676772.92256868465035.390437007
1676698.87973775465023.4478755891676612.49605225465009.514832586
#Sta/Elev= 30
       0 1033.19      32 1022.42    38.6 1017.79    48.7 1007.32    68.8  992.67
    88.8  982.14   102.1   973.7   122.1  963.68     142  959.48   191.8  957.41
   208.6951.7654   221.7  949.88  226.96951.7679     235  958.01   248.3  963.11
   271.6  965.87   298.2  965.56   304.8  966.78   311.5  970.94   318.1  978.56
   323.4  981.17   328.1  980.75   335.9  977.61   346.3  968.71   351.4   966.8
   364.6  971.29   391.2  972.36   397.9  975.13   417.8  991.49   425.1  994.63
#Mann= 4 ,-1,0
       0      .1       0   208.6    .045       0  226.96      .1       0
  252.56     .06       0
Bank Sta=208.6,226.96
XS Rating Curve= 0 ,0
Exp/Cntr(USF)=0,0
Exp/Cntr=0.3,0.1

Type RM Length L Ch R = 1 ,538     ,37.7,39.1,38.4
XS GIS Cut Line= 4
1677037.82350288465008.9756919911676854.67053462464995.610475388
1676775.96425908464942.6446170021676637.85702086 464916.40919182
#Sta/Elev= 30
       0 1037.42     8.1 1033.75    24.5  1028.2    31.1 1024.96    44.3 1013.83
    47.6 1010.38    54.2 1001.07    57.4  997.67    80.5  982.78      87  979.67
   116.7  971.97   133.1   961.5   139.7  958.84     166  955.99   190.1  955.24
   202.5951.6966   209.8  950.03   215.6  950.35   221.4  951.76   229.7  957.36
   266.5  961.86   334.1  964.56   340.8  967.66   350.8  969.35   362.5  972.78
   370.7  977.12   380.9  983.91     385  985.78   407.6   990.5   419.1  994.74
#Mann= 5 ,-1,0
       0      .1       0   202.5    .045       0   221.4      .1       0
  298.51     .06       0  388.51      .1       0
Bank Sta=202.5,221.4
XS Rating Curve= 0 ,0
Exp/Cntr(USF)=0,0
Exp/Cntr=0.3,0.1