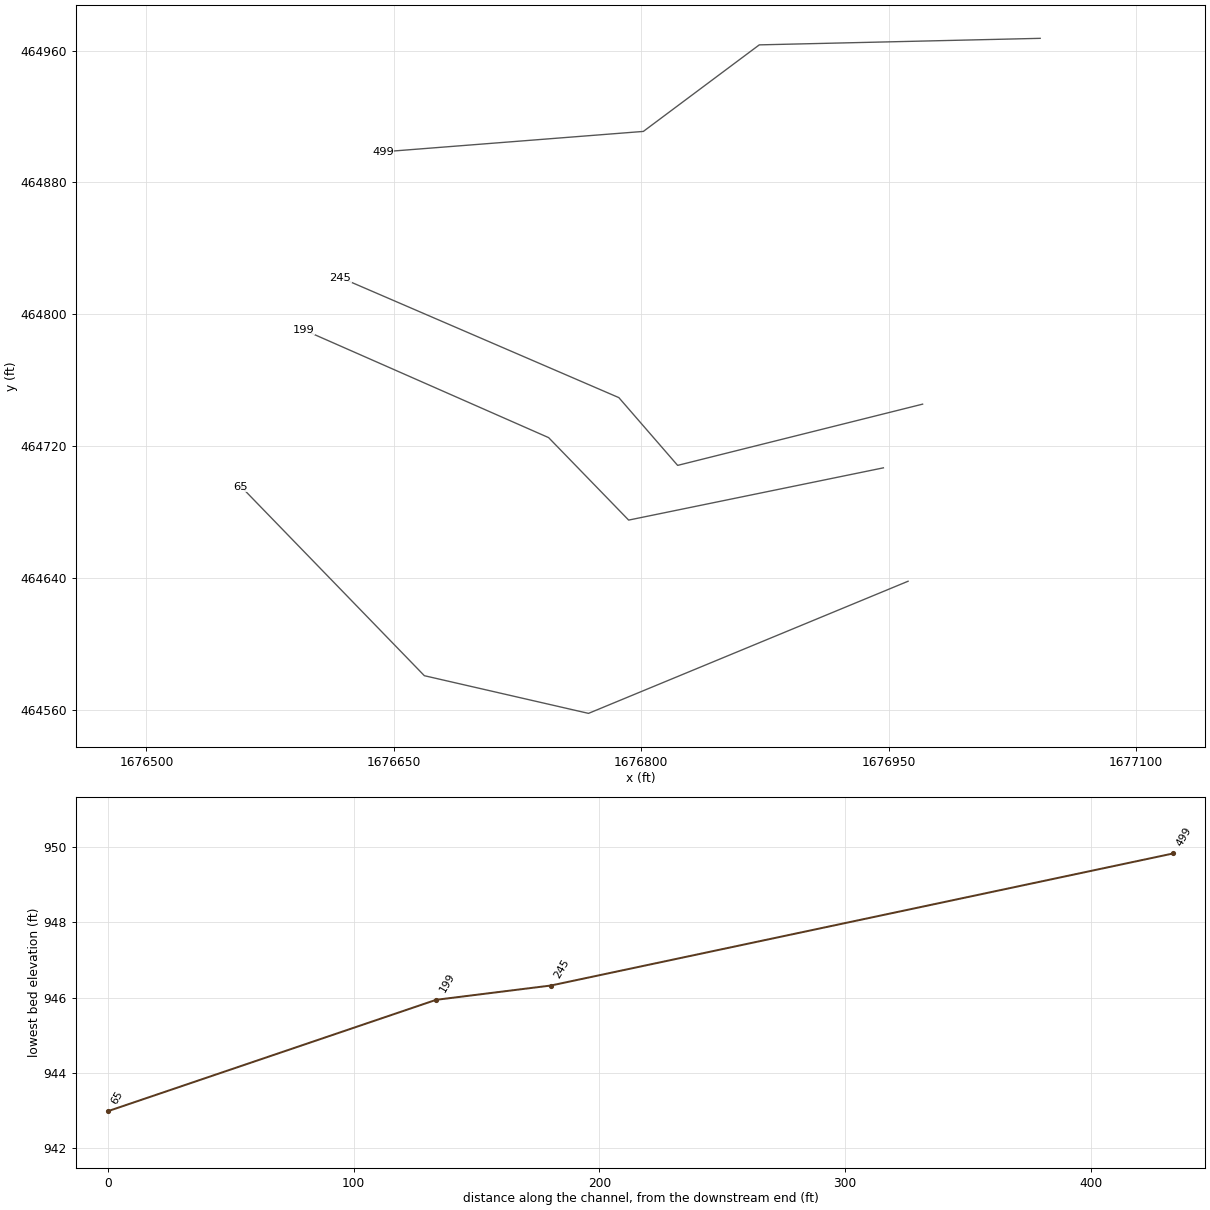
HEC-RAS study FourmileRn.prj: FourmileRn

--- FourmileRn.g01 (geometry) --- (continued)

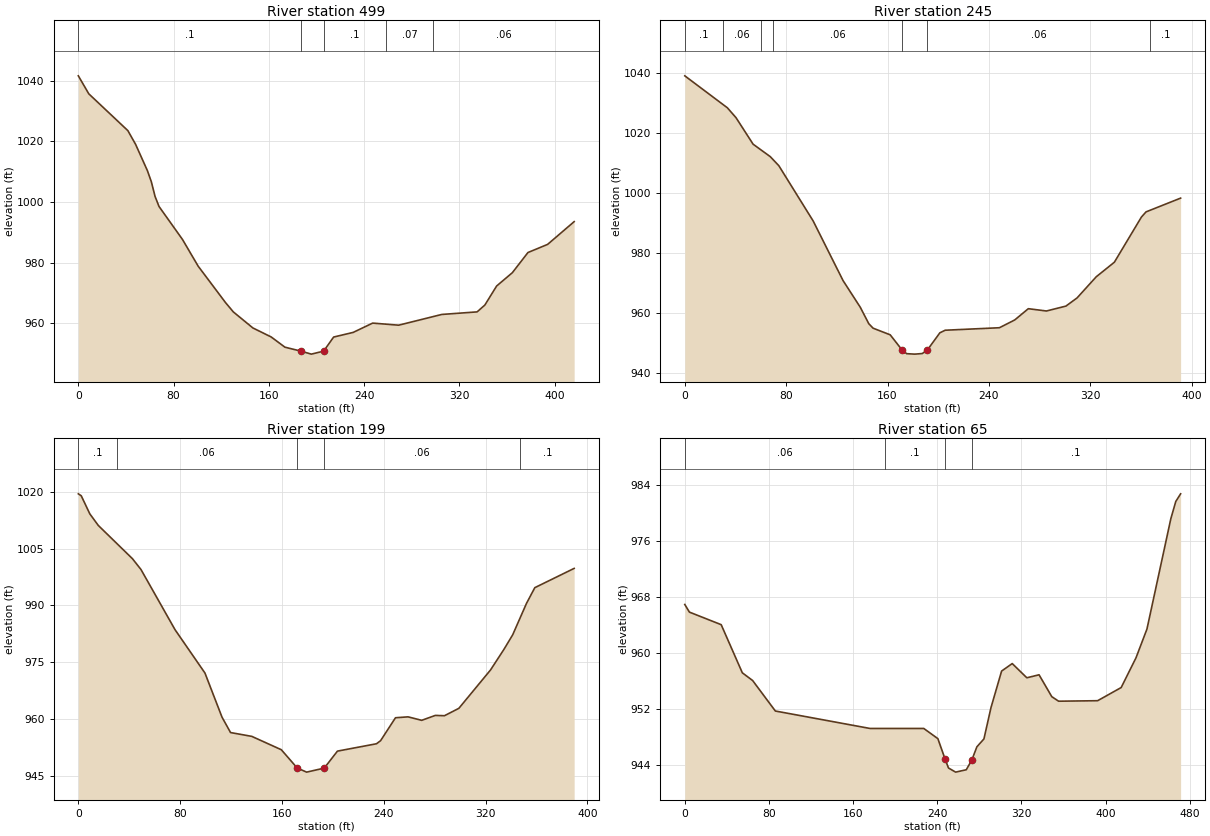
Type RM Length L Ch R = 1 ,499     ,264.2,253.3,234.6
XS GIS Cut Line= 4
1677041.78356705464967.3950181171676871.50080738464963.434953939
1676801.20966822464910.964103575 1676643.3021091464898.588903017
#Sta/Elev= 30
       0 1041.59     8.8 1035.65    41.6 1023.52    48.1    1019      58 1010.33
    61.3 1006.68    64.5 1001.75    67.8  998.49    87.5  987.62   100.6  978.85
   123.6  966.83   130.2  963.74   146.6  958.46     162  955.48   173.5  952.12
   186.8950.8335   195.7  949.83  206.04950.8181   214.4  955.46   230.8  956.99
   247.2  960.06     269  959.37   305.2  962.91   334.9  963.76   341.4  966.01
   351.3  972.29   364.5  976.68   377.6  983.33   394.1  986.01   416.4  993.51
#Mann= 5 ,-1,0
       0      .1       0   186.8    .045       0  206.04      .1       0
  258.04     .07       0  298.04     .06       0
Bank Sta=186.8,206.04
XS Rating Curve= 0 ,0
Exp/Cntr(USF)=0,0
Exp/Cntr=0.3,0.1

Type RM Length L Ch R = 1 ,245     ,46,46.7,46.9
XS GIS Cut Line= 4
1676970.50241184464745.6314241261676822.00000515464708.505822453
1676786.35942755464749.5914883041676617.56169194464822.357667582
#Sta/Elev= 30
       0 1039.12    33.6 1028.46    40.4 1025.18    53.9 1016.33    67.4 1012.19
    74.2 1009.16   101.3  990.73   124.9  970.84   138.5  961.94   145.2  956.47
   148.6  954.97   162.1  952.76   171.4947.7413   175.1  946.47   181.5  946.32
   187.4  946.51   191.5  947.73   201.3  953.43   205.5  954.29   248.3  955.12
   260.4  957.72   271.1  961.47   285.4   960.7   300.8  962.34   309.6  965.07
   324.7  972.11     339  976.96   360.4  992.05     364  993.75   391.3  998.34
#Mann= 7 ,-1,0
       0      .1       0      30     .06       0      60      .1       0
      70     .06       0   171.4    .045       0   191.5     .06       0
  367.46      .1       0
Bank Sta=171.4,191.5
XS Rating Curve= 0 ,0
Exp/Cntr(USF)=0,0
Exp/Cntr=0.3,0.1

Type RM Length L Ch R = 1 ,199     ,131.4,133.6,144.2
XS GIS Cut Line= 4
1676946.74202677464707.0207983861676792.29952381464675.340284958
1676743.78873763464725.3360952111676595.28633094464790.677154155
#Sta/Elev= 30
       0  1019.5     2.3 1018.98       9 1014.22    15.7 1011.14    42.5 1002.36
    49.2  999.51      76  983.58    99.5  972.13   112.9  960.47   119.6   956.4
   136.3  955.39   159.5  951.86  172.01947.0201   179.4  945.94  193.24947.0068
   203.6  951.49   234.3  953.44   237.5  954.25   249.2  960.31   259.1  960.55
   269.8  959.63   280.5  960.93   287.7  960.85     299   962.8   323.9  972.95
   334.3  978.32   341.3  982.23   352.2  990.58   358.7   994.7   389.6  999.79
#Mann= 5 ,-1,0
       0      .1       0      30     .06       0  172.01    .045       0
  193.24     .06       0  347.32      .1       0
Bank Sta=172.01,193.24
XS Rating Curve= 0 ,0
Exp/Cntr(USF)=0,0
Exp/Cntr=0.3,0.1

Type RM Length L Ch R = 1 ,65      ,,,
XS GIS Cut Line= 4
1676961.70188356 464638.27338791 1676767.9613392464558.169124373
1676668.45841196 464581.006350781676557.31600088464695.649463834
#Sta/Elev= 30
       0   966.9     4.4  965.81    34.6  964.02    54.7  957.15    64.5  956.05
    86.1   951.7   176.1  949.21   227.2  949.21   240.6  947.76   247.4  944.87
   250.7  943.57   257.5  942.98   267.6  943.32   272.9  944.71   277.7  946.59
   284.4  947.72   291.1  952.18   301.2   957.4   311.3  958.47   325.2  956.44
   336.8  956.87   348.9  953.75   355.4   953.1   392.5  953.17   414.9  955.05
     429   959.3   439.4   963.4   462.1  979.14   466.8   981.6   471.4  982.69
#Mann= 4 ,-1,0
       0     .06       0     190      .1       0   247.4    .045       0
   272.9      .1       0
Bank Sta=247.4,272.9
XS Rating Curve= 0 ,0
Exp/Cntr(USF)=0,0
Exp/Cntr=0.3,0.1
LCMann Table=0

Chan Stop Cuts=-1
Use User Specified Reach Order=0
Composite Channel Slope=5